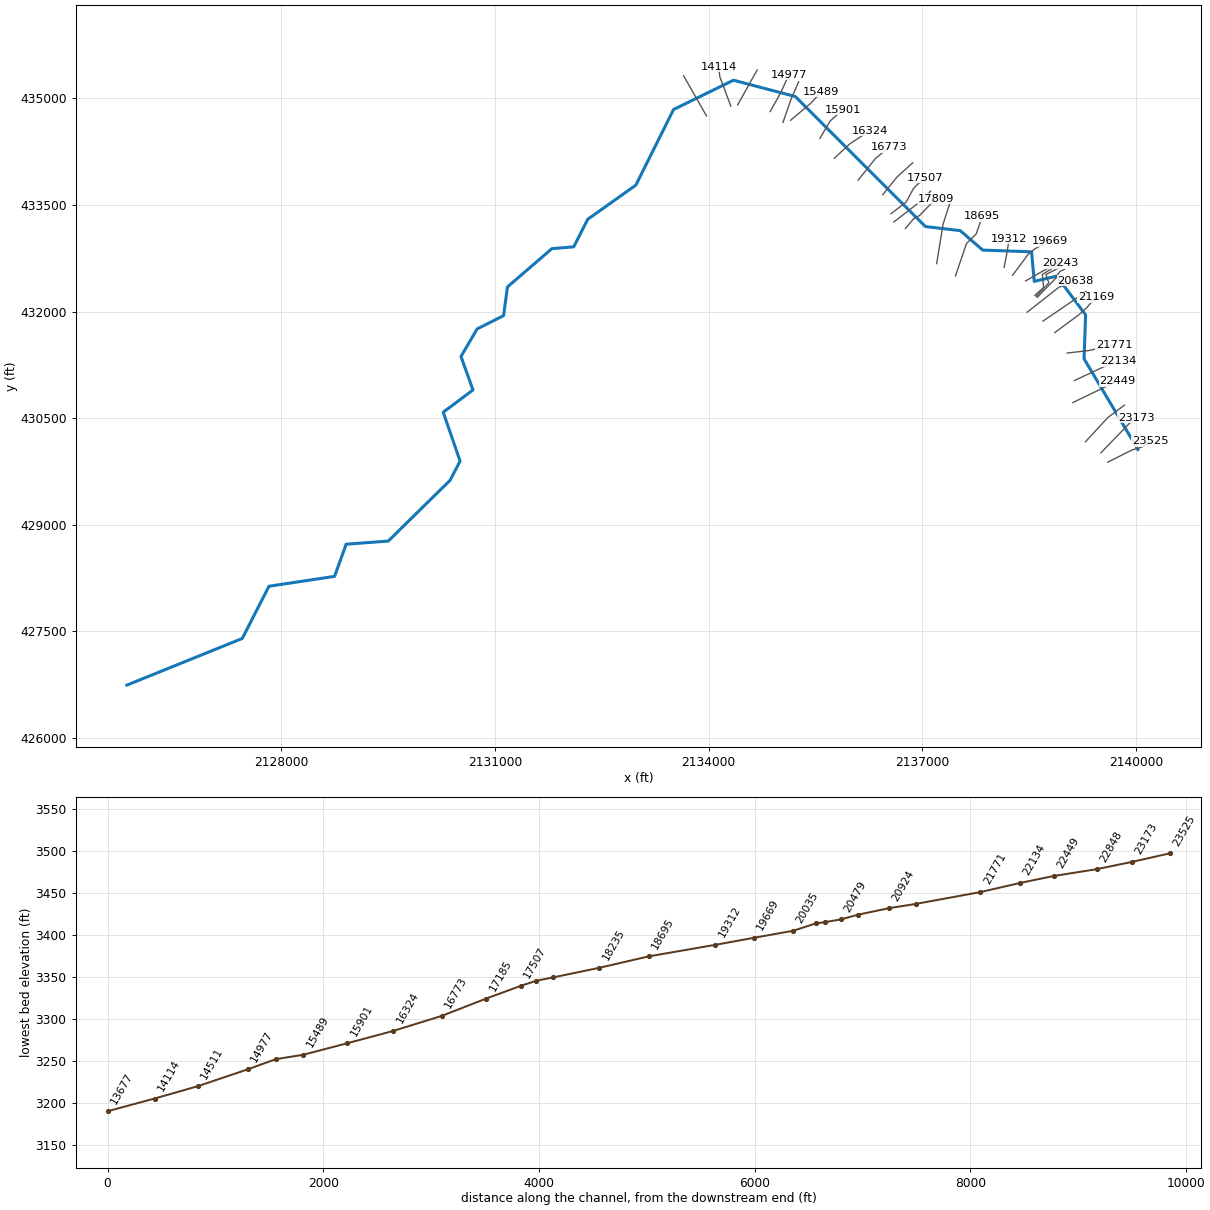
--- ROCKYRN.prj (project) ---

Proj Title=ROCKYRN
Current Plan=p01
Default Exp/Contr=0,0
English Units
Geom File=g01
Flow File=f01
Plan File=p01
BEGIN DESCRIPTION:
Stream Name- Rocky Run
Flood Zone: Zone A
Greenbrier County, WV
County-Wide Study
WVDHSEM-2018-3, Flood Risk Project
HEC-RAS Version: 5.0.7
General Notes:
For the Hydrology Regression was used.
END DESCRIPTION:
DSS Export Rating Curves= 0
DSS Export Rating Curve Sorted= 0
DSS Export Volume Flow Curves= 0
DXF OffsetX= 0
DXF OffsetY= 0
DXF ScaleX= 0
DXF ScaleY= 0

--- ROCKYRN.p01 (plan) ---

Plan Title=Floodplain
Program Version=5.07
Short Identifier=Floodplain
Geom File=g01
Flow File=f01
Subcritical Flow
K Sum by GR= 0
Std Step Tol= 0.01
Critical Tol= 0.01
Num of Std Step Trials= 20
Max Error Tol= 0.3
Flow Tol Ratio= 0.001
Split Flow NTrial= 30
Split Flow Tol= 0.02
Split Flow Ratio= 0.02
Log Output Level= 0
Friction Slope Method= 1
Unsteady Friction Slope Method= 2
Unsteady Bridges Friction Slope Method= 1
Parabolic Critical Depth
Global Vel Dist= 0 , 0 , 0
Global Log Level= 0
CheckData=False
Encroach Param=-1 ,0,0, 0
Mapping Interval=1HOUR
Computation Time Step Use Courant=        0
Computation Time Step Use Time Series=    0
Computation Time Step Count To Double=0
Computation Time Step Max Doubling=0
Computation Time Step Max Halving=0
Computation Time Step Residence Courant=0
Run HTab= 0
Run UNet= 0
Run Sediment= 0
Run PostProcess= 0
Run WQNet= 0
Run RASMapper= 0
UNET Theta= 0
UNET Theta Warmup= 0
UNET ZTol= 0
UNET ZSATol= 0
UNET MxIter= 0
UNET Max Iter WO Improvement= 0
UNET MaxInSteps= 0
UNET DtIC= 0
UNET DtMin= 0
UNET MaxCRTS= 0
UNET WFStab= 0
UNET SFStab= 0
UNET WFX= 1
UNET SFX= 1
UNET 1D Methodology=Finite Difference
UNET DSS MLevel= 1
UNET Pardiso=0
UNET DZMax Abort= 0
UNET Use Existing IB Tables= 0
UNET Froude Reduction=False
UNET Froude Limit= 0
UNET Froude Power= 0
UNET D1 Cores= 0
UNET D2 Coriolis=0
UNET D2 Cores= 0
UNET D2 Theta= 1
UNET D2 Theta Warmup= 1
UNET D2 Z Tol= 0.01
UNET D2 Volume Tol= 0.01
UNET D2 Max Iterations= 20
UNET D2 Equation= 0
UNET D2 RampUpFraction=0.1
UNET D2 TimeSlices= 1
UNET D2 BCVolumeCheck=0
UNET D1D2 MaxIter= 0
UNET D1D2 ZTol=0.01
UNET D1D2 QTol=0.1
UNET D1D2 MinQTol=1
Write IC File= 0
Write IC File at Fixed DateTime=0
Write IC File at Sim End=0
Echo Input=False
Echo Parameters=False
Echo Output=False
Write Detailed= 0
HDF Write Warmup=0
HDF Write Time Slices=0
HDF Flush=0
HDF Face Node Velocities=0
HDF Compression= 1
HDF Chunk Size= 1
HDF Spatial Parts= 1
HDF Use Max Rows=0
HDF Fixed Rows= 1
Calibration Method= 0
Calibration Iterations= 20
Calibration Max Change=0.05
Calibration Tolerance=0.2
Calibration Maximum=1.5
Calibration Minimum=0.5
Calibration Optimization Method= 1
WQ AD Non Conservative
WQ ULTIMATE=-1
WQ Max Comp Step=1HOUR
WQ Output Interval=15MIN
WQ Output Selected Increments= 0
WQ Output face flow=0
WQ Output face velocity=0
WQ Output face area=0
WQ Output face dispersion=0
WQ Output cell volume=0
WQ Output cell surface area=0
WQ Output cell continuity=0
WQ Output cumulative cell continuity=0
WQ Output face conc=0
WQ Output face dconc_dx=0
WQ Output face courant=0
WQ Output face peclet=0
WQ Output face adv mass=0
WQ Output face disp mass=0
WQ Output cell mass=0
WQ Output cell source sink temp=0
WQ Output nsm pathways=0
WQ Output nsm derived pathways=0
WQ Output MaxMinRange=-1
WQ Daily Max Min Mean=-1
WQ Daily Range=0
WQ Daily Time=0
WQ Create Restart=0
WQ Fixed Restart=0
WQ System Summary=0
WQ Write To DSS=0
WQ Use Fixed Temperature=0
Sorting and Armoring Iterations= 10
XS Update Threshold= 0.02
Bed Roughness Predictor= 0
Hydraulics Update Threshold= 0.02
Energy Slope Method= 1
Volume Change Method= 1
Sediment Retention Method= 0
XS Weighting Method= 0
Number of US Weighted Cross Sections= 1
Number of DS Weighted Cross Sections= 1
Upstream XS Weight=0
Main XS Weight=1
Downstream XS Weight=0
Number of DS XS's Weighted with US Boundary= 1
Upstream Boundary Weight= 1
Weight of XSs Associated with US Boundary= 0
Number of US XS's Weighted with DS Boundary= 1
Downstream Boundary Weight= 0.5
Weight of XSs Associated with DS Boundary= 0.5
Percentile Method= 0
Sediment Output Level= 3
Mass or Volume Output= 0
Output Increment Type= 1
Profile and TS Output Increment= 1
XS Output Flag= 0
XS Output Increment= 10
Write Gradation File= 0
Read Gradation Hotstart= 0
Write HDF5 File= 1
Write Binary Output= 1
Write DSS Sediment File= 0
SV Curve= 0
Specific Gage Flag= 0

--- ROCKYRN.f01 (steady flow) ---

Flow Title=NFF Regression Equation
Program Version=5.07
Number of Profiles= 6
Profile Names=f1p,f10p,f4p,f2p,f02p,f1pplus
River Rch & RM=ROCKYRN,Main            ,23525
     561     296     394     475     785     830
River Rch & RM=ROCKYRN,Main            ,21169
     631     334     444     534     879     933
River Rch & RM=ROCKYRN,Main            ,19312
     857     460     607     728    1190    1270
River Rch & RM=ROCKYRN,Main            ,18695
     956     515     679     813    1320    1410
River Rch & RM=ROCKYRN,Main            ,13677
    1230     669     878    1050    1690    1820
River Rch & RM=ROCKYRN,Main            ,11780
    1390     760     993    1180    1910    2050
River Rch & RM=ROCKYRN,Main            ,6110
    1690     932    1220    1450    2320    2500
Boundary for River Rch & Prof#=ROCKYRN,Main            , 1
Up Type= 0
Dn Type= 3
Dn Slope=0.02593
Boundary for River Rch & Prof#=ROCKYRN,Main            , 2
Up Type= 0
Dn Type= 3
Dn Slope=0.02593
Boundary for River Rch & Prof#=ROCKYRN,Main            , 3
Up Type= 0
Dn Type= 3
Dn Slope=0.02593
Boundary for River Rch & Prof#=ROCKYRN,Main            , 4
Up Type= 0
Dn Type= 3
Dn Slope=0.02593
Boundary for River Rch & Prof#=ROCKYRN,Main            , 5
Up Type= 0
Dn Type= 3
Dn Slope=0.02593
Boundary for River Rch & Prof#=ROCKYRN,Main            , 6
Up Type= 0
Dn Type= 3
Dn Slope=0.02593
DSS Import GetInterval= 0
DSS Import GetPeak= 0
DSS Import FillOption= 0

--- ROCKYRN.g01 (geometry) ---

Geom Title=USGS 10m DEM
Program Version=5.07

River Reach=ROCKYRN         ,Main
Reach XY= 30
     2140028.126      430058.242      2139272.12      431334.842
     2139293.635      431953.8612138886.87990544432498.504204662
     2138572.522      432424.8222138534.46160622432840.716409324
     2137848.184      432865.015     2137533.052      433139.082
     2137043.986      433196.329     2135217.328      435026.018
     2134349.042      435255.786     2133507.869      434843.501
     2132978.241      433779.021     2132302.683      433298.347
     2132106.319      432910.863     2131799.744      432885.496
     2131175.701      432346.784     2131121.164      431942.661
     2130749.129      431754.645     2130522.902       431368.18
     2130691.537      430896.551     2130273.531      430583.454
     2130510.526      429895.095     2130369.908      429625.369
     2129502.101       428770.15     2128910.665      428725.792
     2128748.048      428273.167     2127827.211      428134.311
2127451.95733403427399.347661819 2125831.1726633426742.636208314

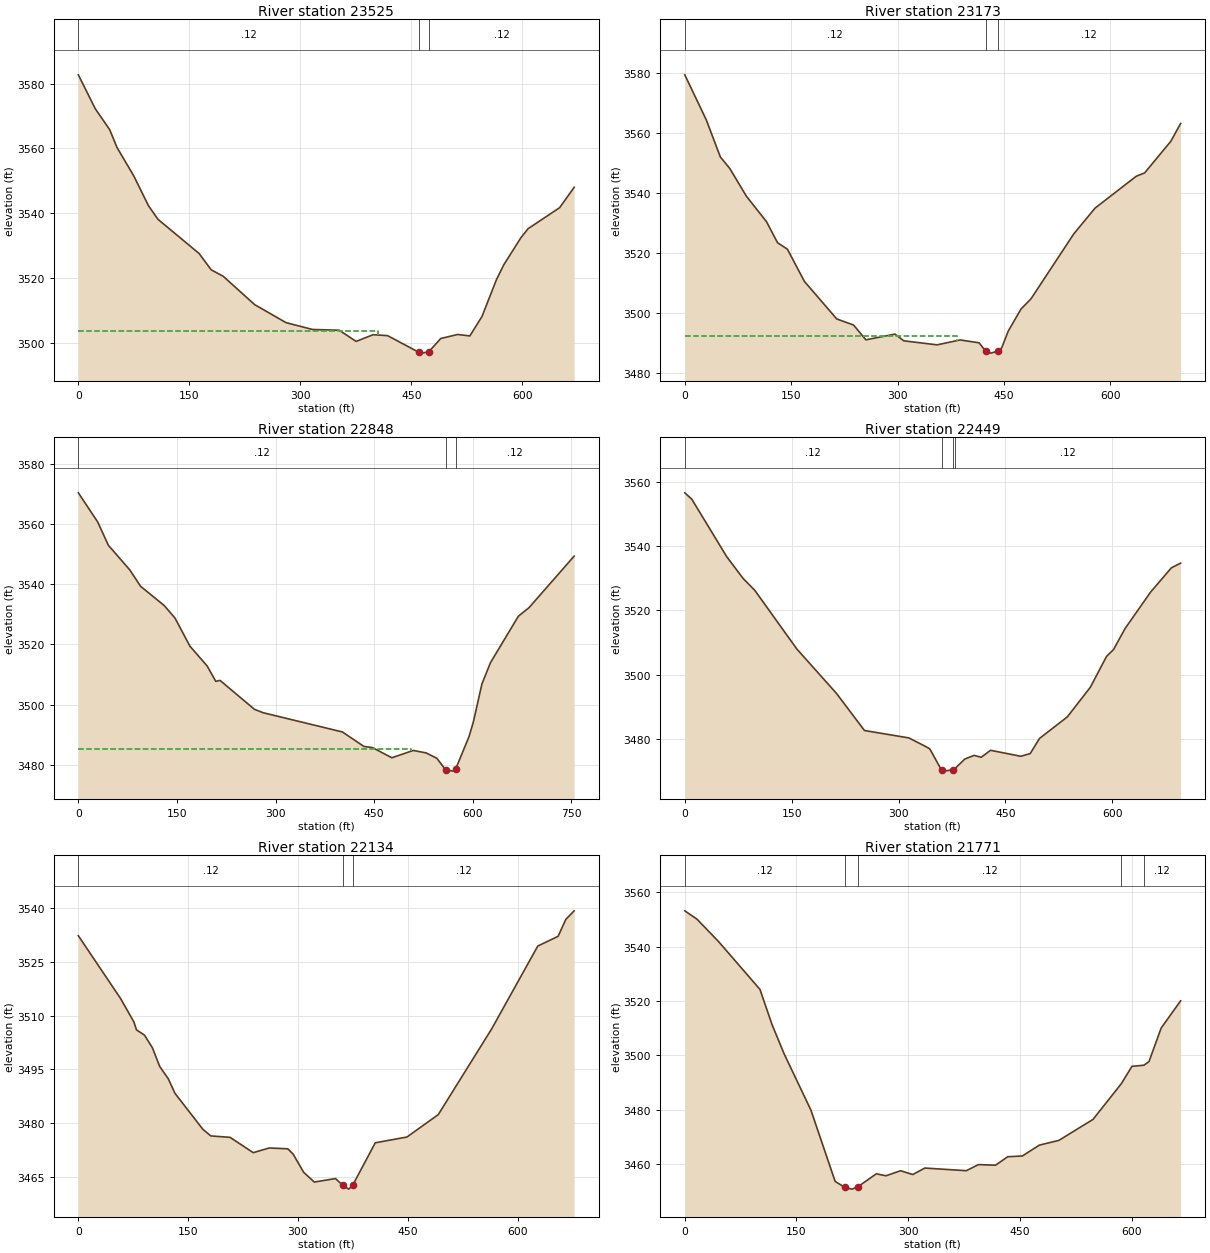
Type RM Length L Ch R = 1 ,23525   ,349.2,351.5,355.7
XS GIS Cut Line= 4
     2139604.136      429880.044     2139945.316      430051.844
     2140083.239      430092.979     2140201.805      430175.249
#Sta/Elev= 30
       0 3582.68    22.8 3572.25    42.4 3565.74    52.2 3560.28    75.1  3551.4
    94.7  3542.3   107.7 3538.05   163.2 3527.52   179.6 3522.47   195.9 3520.46
   238.3 3511.72   280.8 3506.15   316.7 3504.04   352.6 3503.82   375.5 3500.36
   398.4 3502.43     418 3502.14   460.5 3496.98   463.8 3496.74   473.6 3497.13
   489.9 3501.26   512.8  3502.5   529.2 3502.05   545.6 3508.05   565.3  3519.5
   575.1 3524.02   598.1 3532.34   607.9 3535.16   650.6 3541.66   670.2 3547.95
#Mann= 3 ,-1 , 0
       0     .12       0   460.5     .04       0   473.6     .12       0
#XS Ineff= 2 , 0
          404.78 3503.42
Permanent Ineff=
       F       F
Bank Sta=460.5,473.6
XS Rating Curve= 0 ,0
Exp/Cntr=0.3,0.1

Type RM Length L Ch R = 1 ,23173   ,323.7,324.9,319.7
XS GIS Cut Line= 3
2139508.38531946430012.3914918222139913.63231323430431.693294632
 2140000.3036356430508.994744312
#Sta/Elev= 30
       0 3579.31    30.3  3564.3    50.1 3551.97    63.6 3548.05    86.8 3538.89
   115.3 3530.36   130.8 3523.37   144.8 3521.19   168.7 3510.48   214.3 3497.97
     238 3495.95   255.4 3491.01   296.5 3492.92   308.8 3490.68   355.8 3489.34
   388.4 3490.97   415.1 3490.02   424.2 3487.26   431.6 3486.58   441.8 3487.25
     447 3488.37   456.2 3493.92   474.2 3501.28   488.2 3504.65   548.5 3526.28
   578.6  3534.9   636.7 3545.51   648.6 3546.64   685.5 3557.17   699.3  3563.1
#Mann= 3 , 0 , 0
       0     .12       0   424.2     .04       0   441.8     .12       0
#XS Ineff= 2 , 0
          383.52 3492.22
Permanent Ineff=
       F       F
Bank Sta=424.2,441.8
XS Rating Curve= 0 ,0
Exp/Cntr(USF)=0,0
Exp/Cntr=0.3,0.1

Type RM Length L Ch R = 1 ,22848   ,401.2,399.1,398.1
XS GIS Cut Line= 3
     2139291.994       430167.99     2139604.136      430506.749
     2139838.848      430683.388
#Sta/Elev= 30
       0  3570.3    29.4 3560.67    45.7 3552.91    78.4 3544.71    94.7 3539.31
   130.7 3532.91     147 3528.79   169.9 3519.41     196 3512.88   209.1 3507.78
   215.6 3508.09   267.9 3498.51     281 3497.38   401.8 3490.99   434.5 3486.19
   447.6  3485.8     477 3482.43   509.6 3484.86   529.2 3484.04   545.5 3482.26
   559.3  3478.3   571.6    3478   574.3 3478.79   594.5 3489.48     601 3494.28
     614 3506.85   627.1 3513.98   669.5 3529.37   685.8 3532.23   754.4 3549.31
#Mann= 3 ,-1 , 0
       0     .12       0   559.3     .04       0   574.3     .12       0
#XS Ineff= 2 , 0
          506.09 3485.48
Permanent Ineff=
       F       F
Bank Sta=559.3,574.3
XS Rating Curve= 0 ,0
Exp/Cntr=0.3,0.1

Type RM Length L Ch R = 1 ,22449   ,317.8,314.7,315.3
XS GIS Cut Line= 3
     2139115.355      430719.684     2139560.582      430935.038
      2139742.06      431022.148
#Sta/Elev= 30
       0 3556.68     9.8  3554.7      59 3536.71    81.9 3529.96    98.3 3526.25
   157.2 3507.98   212.9 3494.11   252.2 3482.54   314.4 3480.23   337.4 3477.63
   343.9  3476.8   360.3 3470.19   363.6 3469.87   376.7 3470.31   379.5 3470.74
     393 3473.64   406.1 3474.78     416 3474.18   429.1 3476.37   471.6  3474.5
   484.8 3475.34   497.8 3480.06   536.8 3486.77   569.2 3496.03     592 3505.69
   601.7 3507.78     618 3514.37   653.7  3525.7   682.9 3533.28   695.9 3534.75
#Mann= 4 ,-1 , 0
       0     .12       0   360.3     .04       0   376.7     .12       0
   379.5     .12       0
Bank Sta=360.3,376.7
XS Rating Curve= 0 ,0
Exp/Cntr=0.3,0.1

Type RM Length L Ch R = 1 ,22134   ,368.3,363.3,361.4
XS GIS Cut Line= 3
2139135.93288009431029.0226785222139559.91961924431228.132473153
 2139756.6869457431298.406518316
#Sta/Elev= 30
       0 3532.29    57.8 3514.73    75.9 3508.22    79.5 3505.99    90.4 3504.53
   101.2 3501.01   111.1 3495.82     123 3492.31     132 3488.29   170.1 3478.25
     181 3476.39   207.3 3475.99     239 3471.71   260.8 3473.02   286.1 3472.79
   293.4 3471.33   307.9 3466.22   322.4  3463.5   351.4 3464.48   361.1 3462.61
   369.5 3461.53   374.7 3462.57   405.7 3474.47     449 3476.08   491.8 3482.35
   564.9 3506.34   627.7  3529.4   655.5 3532.13     666 3536.85   677.4 3539.24
#Mann= 3 , 0 , 0
       0     .12       0   361.1     .04       0   374.7     .12       0
Bank Sta=361.1,374.7
XS Rating Curve= 0 ,0
Exp/Cntr(USF)=0,0
Exp/Cntr=0.3,0.1

Type RM Length L Ch R = 1 ,21771   ,597.9,601.9,609
XS GIS Cut Line= 3
     2139035.505       431416.56     2139333.129      431450.436
     2139691.246      431527.867
#Sta/Elev= 30
       0 3553.18    16.3 3550.14    45.6 3541.79   100.9  3524.3   117.2 3511.31
   133.5 3500.51   169.3 3479.94   201.9 3453.65   214.9 3451.47   224.7 3450.81
   232.7 3451.72   257.2 3456.44   270.2 3455.72   289.8 3457.58   306.1 3456.18
   322.4 3458.56   378.1 3457.59   394.4 3459.83   417.3 3459.61   433.7 3462.72
   453.3    3463   476.2    3467   502.4 3468.74   548.2 3476.45  586.38 3489.64
   600.5 3495.97   616.6 3496.39   623.4 3497.72   639.8 3510.07   665.9 3520.08
#Mann= 5 ,-1 , 0
       0     .12       0   214.9     .04       0   232.7     .12       0
  586.38    .016       0   616.6     .12       0
Bank Sta=214.9,232.7
XS Rating Curve= 0 ,0
Exp/Cntr=0.3,0.1

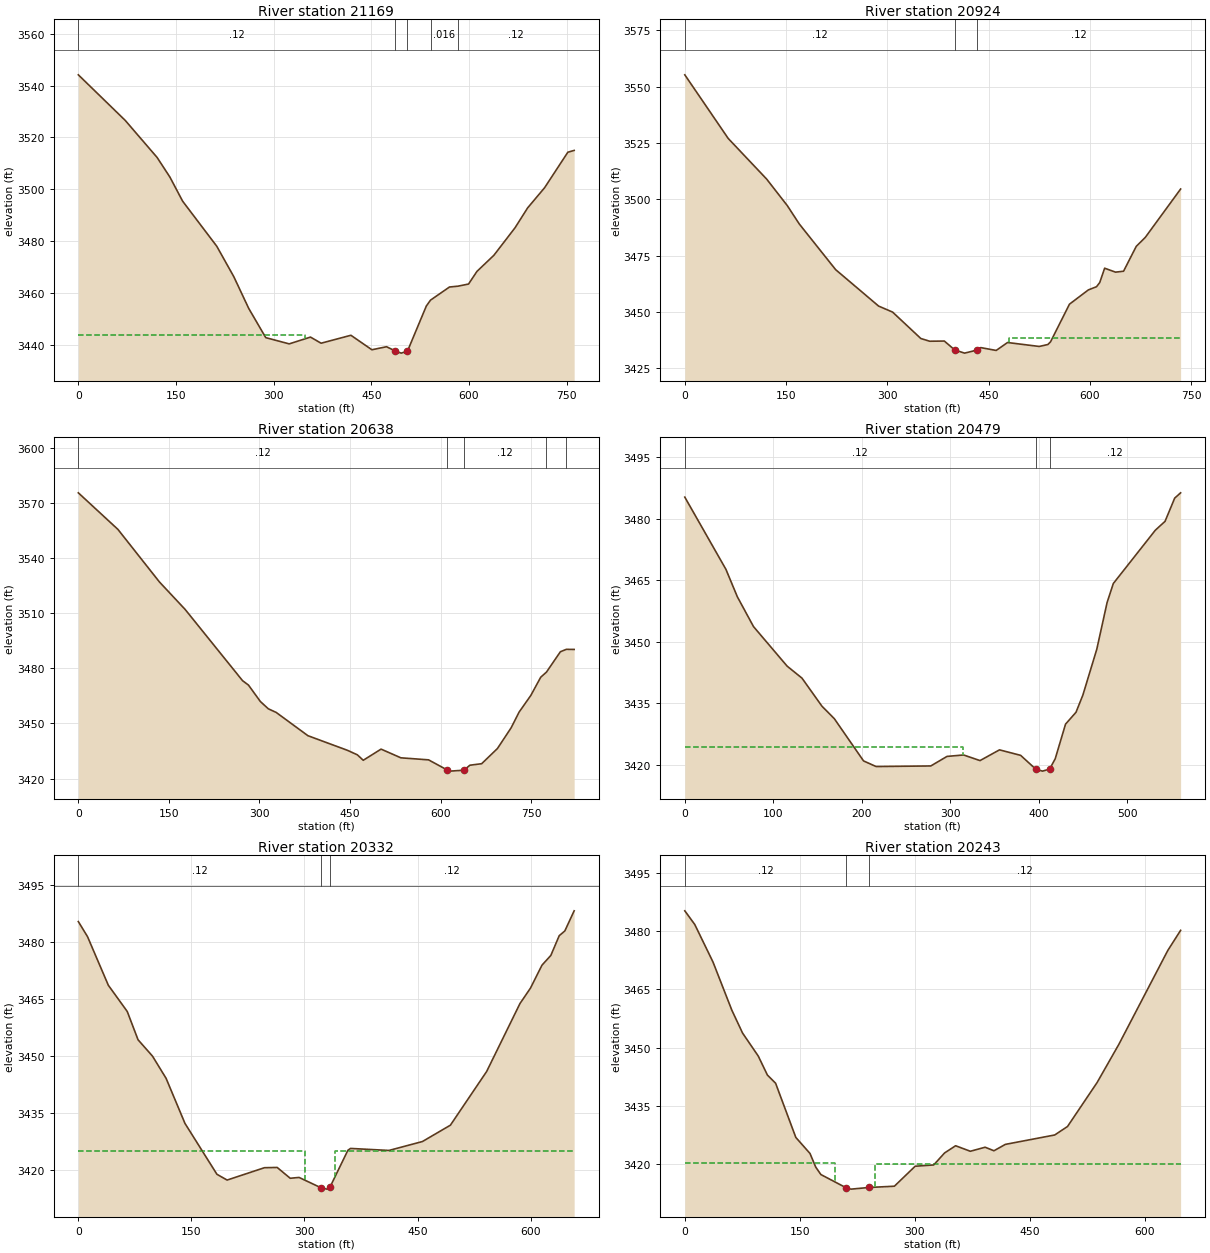
Type RM Length L Ch R = 1 ,21169   ,250.7,245.4,239.4
XS GIS Cut Line= 4
     2138861.285      431704.506     2139197.625      431953.736
     2139294.414      432038.426     2139437.176      432198.127
#Sta/Elev= 30
       0 3544.14      72 3526.55     121 3512.23   140.6 3504.67   160.2 3495.35
   212.6 3477.96   238.7 3466.24   261.6 3453.99   287.8 3442.68   323.8 3440.27
   356.5 3442.89   372.8 3440.53   418.6 3443.59   450.8    3438   473.3 3439.17
   486.1 3437.61   495.8  3436.7   505.4 3437.43   534.4 3454.89   540.9 3457.17
     570 3462.23  582.81 3462.54   599.2 3463.37   612.1 3468.24   638.1 3474.46
   670.6 3485.09     690 3492.78     716 3500.55   751.7 3514.26   761.4 3514.96
#Mann= 5 ,-1 , 0
       0     .12       0   486.1     .04       0   505.4     .12       0
   540.9    .016       0  582.81     .12       0
#XS Ineff= 2 , 0
           348.7 3443.73
Permanent Ineff=
       F       F
Bank Sta=486.1,505.4
XS Rating Curve= 0 ,0
Exp/Cntr=0.3,0.1

Type RM Length L Ch R = 1 ,20924   ,286.7,286,276.1
XS GIS Cut Line= 3
2138695.54886373431865.2838159692139157.01509364432181.517019205
2139299.90565214432282.243150606
#Sta/Elev= 30
       0 3555.22    64.3 3526.98   121.3 3508.92   151.8 3497.17   169.5 3489.04
   223.4 3468.75     287 3452.59   307.7 3449.92   349.5  3438.2   362.6 3436.99
   384.3 3437.07   399.7 3433.12   414.3 3431.71   432.13433.017   438.2 3434.16
   461.1  3432.9   477.9 3436.42   524.8 3434.67   537.6 3435.53   541.6 3436.74
   569.6 3453.43   597.6 3459.77   609.7 3461.19   614.4 3463.02   621.7  3469.4
   637.8 3467.65   649.7 3468.06   668.5 3479.09   681.9 3483.08   734.2 3504.54
#Mann= 3 , 0 , 0
       0     .12       0   399.7     .04       0   432.1     .12       0
#XS Ineff= 2 , 0
                             480         3438.22
Permanent Ineff=
       F       F
Bank Sta=399.7,432.1
XS Rating Curve= 0 ,0
Exp/Cntr(USF)=0,0
Exp/Cntr=0.3,0.1

Type RM Length L Ch R = 1 ,20638   ,154.2,158.8,166.7
XS GIS Cut Line= 4
     2138471.712      431990.032     2138922.338      432344.831
     2139091.078      432405.244     2139152.533      432435.451
#Sta/Elev= 30
       0 3575.65    65.6 3555.72   134.4 3527.06     177 3512.08     272  3473.3
   281.8  3470.9   301.5 3461.95   314.6 3457.99   327.7    3456   380.2 3443.33
   445.7 3435.36   462.1 3432.91   471.9 3429.93   501.4 3436.01   534.2 3431.27
   580.1 3430.16   611.3 3424.58   615.9 3424.02   638.7 3424.53   648.5 3427.24
     668 3428.06   694.1 3436.32   716.9 3447.66     730 3456.17   749.5  3465.3
   765.8 3475.18  775.38    3478   798.4 3489.07  808.29 3490.38   821.2 3490.32
#Mann= 5 ,-1 , 0
       0     .12       0   611.3     .04       0   638.7     .12       0
  775.38    .016       0  808.29     .12       0
Bank Sta=611.3,638.7
XS Rating Curve= 0 ,0
Exp/Cntr=0.3,0.1

Type RM Length L Ch R = 1 ,20479   ,140.5,147.3,153.9
XS GIS Cut Line= 4
2138614.54309099432200.6065021772138862.09522053432456.230983772
2138932.05560497432563.862344443 2139000.6705974432597.497144653
#Sta/Elev= 30
       0 3485.24    46.5 3467.63    59.4 3460.94    77.7 3453.66   115.7 3444.02
   132.5 3441.09   155.1 3434.24     169 3431.22   202.1  3420.9   216.3 3419.53
   278.1 3419.67   296.5    3422   315.2 3422.35   333.8 3420.98   355.8  3423.6
   379.7 3422.26     397 3418.86   404.5 3418.41   412.5 3418.91   418.8 3421.42
   430.5 3429.88   442.3 3432.76   450.1 3436.97   465.8 3448.13   477.5 3459.56
   484.5 3464.17     532 3477.17     543 3479.34   553.9    3485   560.6 3486.29
#Mann= 3 ,-1 , 0
       0     .12       0     397     .04       0   412.5     .12       0
#XS Ineff= 2 , 0
          314.13 3424.23
Permanent Ineff=
       F       F
Bank Sta=397,412.5
XS Rating Curve= 0 ,0
Exp/Cntr=0.3,0.1

Type RM Length L Ch R = 1 ,20332   ,99.7,88.1,85.1
XS GIS Cut Line= 4
2138599.20206363432214.2419824772138777.06890188432403.531461713
2138736.27375549432520.2055803812138979.41282796432647.486437108
#Sta/Elev= 30
       0 3485.32    12.2 3481.36    39.8 3468.61    64.9 3461.72    79.2 3454.31
    98.4    3450   116.4 3444.19   141.5 3432.34   183.9 3418.99   197.4 3417.48
   246.9 3420.72   263.8 3420.79   281.1 3417.95   292.8 3418.17   321.43415.509
   329.8  3415.1     334 3415.68   357.6 3425.29   361.1 3425.78   412.1 3425.25
   456.5 3427.59   493.6 3431.88   541.7 3445.97   585.9  3463.8   599.8 3467.84
   615.1 3473.87   626.9 3476.45     638 3481.62   645.4 3482.85   657.8 3488.14
#Mann= 3 , 0 , 0
       0     .12       0   321.4     .04       0     334     .12       0
#XS Ineff= 2 , 0
          300.89 3425.18  339.87         3425.18
Permanent Ineff=
       F       F
Bank Sta=321.4,334
XS Rating Curve= 0 ,0
Exp/Cntr(USF)=0,0
Exp/Cntr=0.3,0.1

Type RM Length L Ch R = 1 ,20243   ,221,208.4,199.3
XS GIS Cut Line= 4
2138581.45397453432228.6205495872138703.33576991432337.407606619
 2138686.2118813  432522.74851862138940.04834771432677.870803628
#Sta/Elev= 30
       0 3485.18      13 3481.67    36.8 3472.01    61.3 3459.66    75.3 3453.76
    95.9  3447.8   107.8 3442.93   118.5 3440.82   144.9 3426.87   163.4 3422.75
   170.9 3419.23   177.6 3417.33   210.9 3413.89   217.1 3413.58     240    3414
   273.5 3414.33   300.6 3419.47   324.8  3419.8     339 3422.89   353.4 3424.74
   372.6 3423.32   391.9 3424.36   403.4 3423.45   418.3 3425.09   482.7 3427.51
   499.4 3429.69     538    3441   566.3 3450.79   630.2 3474.96     647 3480.16
#Mann= 3 , 0 , 0
       0     .12       0   210.9     .04       0     240     .12       0
#XS Ineff= 2 , 0
          195.66 3420.29  248.66         3420.03
Permanent Ineff=
       F       F
Bank Sta=210.9,240
XS Rating Curve= 0 ,0
Exp/Cntr(USF)=0,0
Exp/Cntr=0.3,0.1

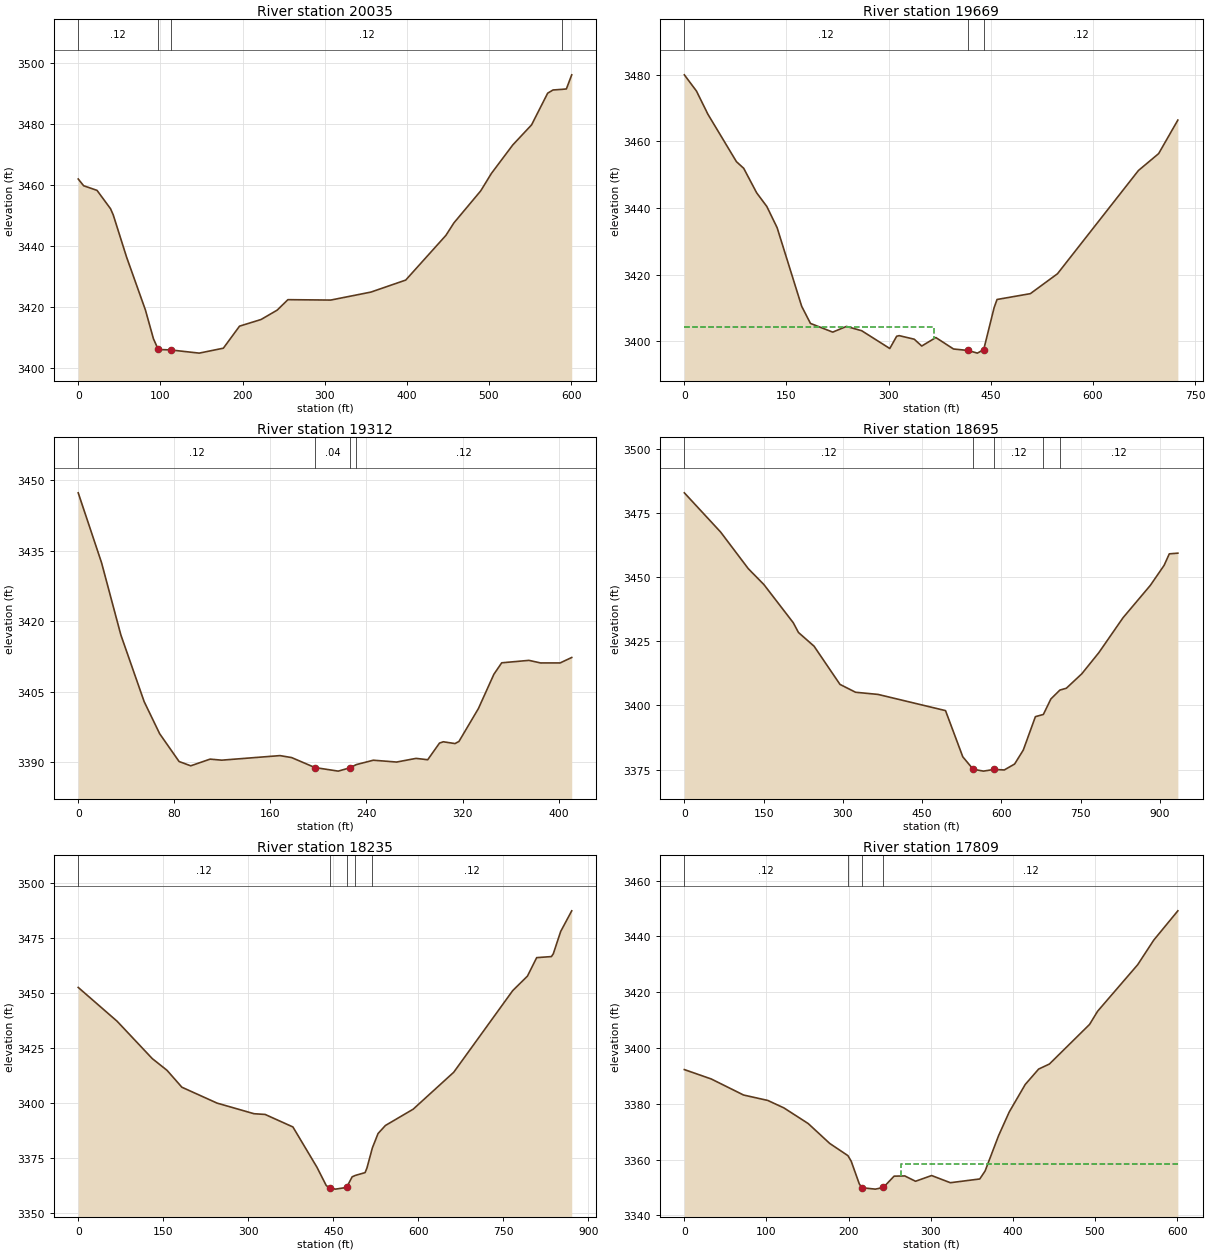
Type RM Length L Ch R = 1 ,20035   ,363.6,366.4,371
XS GIS Cut Line= 3
     2138450.623       432430.99     2138674.947      432559.584
      2138973.57      432726.755
#Sta/Elev= 30
       0 3461.93     6.6 3459.72    22.9  3458.2    39.3  3452.2    42.6  3450.2
    58.9 3436.32    81.8 3419.01    91.6 3409.56    97.4 3406.05   112.4 3405.91
   147.3 3404.86   176.7 3406.48   196.4  3413.7   222.6 3415.88   242.2 3418.95
   255.3 3422.38   307.5 3422.25   356.4 3424.87   398.7  3428.8   447.6 3443.44
   457.4 3447.55     490 3458.04     503 3463.75   529.1 3473.11   551.9 3479.66
   571.5 3490.05     578  3491.1  589.48 3491.32   594.3 3491.45   600.8 3496.07
#Mann= 4 ,-1 , 0
       0     .12       0    97.4     .04       0   112.4     .12       0
  589.48    .016       0
Bank Sta=97.4,112.4
XS Rating Curve= 0 ,0
Exp/Cntr=0.3,0.1

Type RM Length L Ch R = 1 ,19669   ,353.4,356.9,367.4
XS GIS Cut Line= 4
2138268.66107639432511.1595192252138487.91014442432806.813565514
2138578.53475352432881.2416480062138789.94965372432993.487703266
#Sta/Elev= 30
       0 3480.02    17.8 3475.15    34.6 3468.19    76.5 3453.94    87.2 3451.94
   106.2 3444.58   121.1 3440.49   136.2 3434.14   172.3 3410.51   185.2 3405.36
   217.9 3402.75   238.1 3404.46   260.4 3403.17   301.7 3397.83   311.8 3401.51
   315.5 3401.69   337.6 3400.62   348.6 3398.57   369.3 3401.12   395.3 3397.68
   416.7 3397.24   430.3 3396.44   439.6 3397.49   454.9  3410.1   459.2 3412.55
   508.1  3414.3   547.9 3420.27   666.8 3451.28   696.5 3456.36   724.7 3466.43
#Mann= 3 ,-1 , 0
       0     .12       0   416.7     .04       0   439.6     .12       0
#XS Ineff= 2 , 0
          366.78 3404.17
Permanent Ineff=
       F       F
Bank Sta=416.7,439.6
XS Rating Curve= 0 ,0
Exp/Cntr=0.3,0.1

Type RM Length L Ch R = 1 ,19312   ,624.7,616.9,599.3
XS GIS Cut Line= 3
     2138149.144      432622.451     2138183.435      432796.767
     2138222.013      433026.806
#Sta/Elev= 30
       0 3447.29    19.4 3432.46    35.5 3417.08    54.9  3402.9    67.8 3396.08
      84 3390.16    93.7 3389.25   109.8 3390.67   119.5 3390.45     168 3391.42
   177.7    3391   197.1 3388.88   216.5 3388.12   226.2 3388.83   231.6 3389.51
   245.7 3390.44   265.1 3390.05   281.3 3390.83     291 3390.54   300.8 3394.08
     304 3394.36   313.7 3393.98     317 3394.43   333.2 3401.42   346.1 3408.72
   352.6 3411.15   375.3 3411.67     385 3411.12   401.2 3411.12   410.9 3412.28
#Mann= 4 ,-1 , 0
       0     .12       0   197.1     .04       0   226.2     .12       0
   231.6     .12       0
#XS Ineff= 2 , 0
          165.63 3391.26
Permanent Ineff=
       F       F
Bank Sta=197.1,226.2
XS Rating Curve= 0 ,0
Exp/Cntr=0.3,0.1

Type RM Length L Ch R = 1 ,18695   ,448.8,459.6,472.3
XS GIS Cut Line= 4
      2137466.17      432501.002     2137620.482      432956.794
     2137757.648      433092.531     2137841.948      433338.288
#Sta/Elev= 30
       0 3482.86    68.7 3467.57   121.1 3453.29   150.6 3447.11   206.2 3432.23
     216 3428.44   245.5  3423.1   294.6 3408.21   324.1 3405.15   366.6 3404.31
   494.3    3398     527 3379.99   546.6 3375.15   566.2 3374.42   585.9 3375.08
   605.5 3374.88   625.1 3377.19   641.5 3382.64   664.4 3395.64   679.5 3396.51
   693.7 3402.54  710.73    3406   722.9 3406.71   752.1 3412.32   784.6 3420.62
   830.1 3434.15     882 3446.82     908  3454.6   917.8 3459.08     934 3459.35
#Mann= 5 ,-1 , 0
       0     .12       0   546.6     .04       0   585.9     .12       0
   679.5    .016       0  710.73     .12       0
Bank Sta=546.6,585.9
XS Rating Curve= 0 ,0
Exp/Cntr=0.3,0.1

Type RM Length L Ch R = 1 ,18235   ,438.7,426.1,414.2
XS GIS Cut Line= 3
     2137201.839      432673.889     2137291.855      433228.269
     2137386.157      433522.605
#Sta/Elev= 30
       0 3452.42    68.6 3437.06   130.6  3420.1   156.7 3414.76   182.9 3407.09
   244.9 3399.88   310.2 3395.05   329.8 3394.72   378.8 3389.04   421.2 3370.74
   437.6 3362.43   444.1 3361.28   453.9  3360.8   473.5 3361.56   483.3 3366.38
  489.07 3367.04   506.1  3368.3   509.4 3370.38  518.99 3379.54     529 3386.05
     542 3389.71   590.9  3397.1   662.5 3413.88   766.6 3450.97   792.6 3457.56
   808.9 3465.95   834.9 3466.43   838.2  3467.7   851.2 3477.83   870.7 3487.21
#Mann= 5 ,-1 , 0
       0     .12       0   444.1     .04       0   473.5     .12       0
  489.07    .016       0  518.99     .12       0
Bank Sta=444.1,473.5
XS Rating Curve= 0 ,0
Exp/Cntr=0.3,0.1

Type RM Length L Ch R = 1 ,17809   ,154.9,158,161.4
XS GIS Cut Line= 4
     2136763.008      433168.569     2136879.668      433306.061
     2136965.079      433353.975     2137187.983      433587.295
#Sta/Elev= 30
       0  3392.3    32.8 3388.93    72.1 3383.18   101.6 3381.24   121.3 3378.55
   150.8 3372.96     177 3365.83  199.23 3361.44   203.2 3359.44     213 3351.33
   216.2 3349.94   232.6 3349.45   242.3 3350.04   255.4  3354.1   268.4 3354.18
   281.5 3352.27   301.1 3354.32   323.9 3351.75   359.7 3353.09   366.2 3355.95
   382.6  3368.6   395.6 3377.11   415.1 3386.97   431.4 3392.48   444.5 3394.29
   493.4 3408.48   503.2 3413.21     552 3429.89   571.6 3438.72   600.9  3449.2
#Mann= 4 ,-1 , 0
       0     .12       0  199.23    .016       0   216.2     .04       0
   242.3     .12       0
#XS Ineff= 2 , 0
                          264.34         3358.51
Permanent Ineff=
       F       F
Bank Sta=216.2,242.3
XS Rating Curve= 0 ,0
Exp/Cntr=0.3,0.1

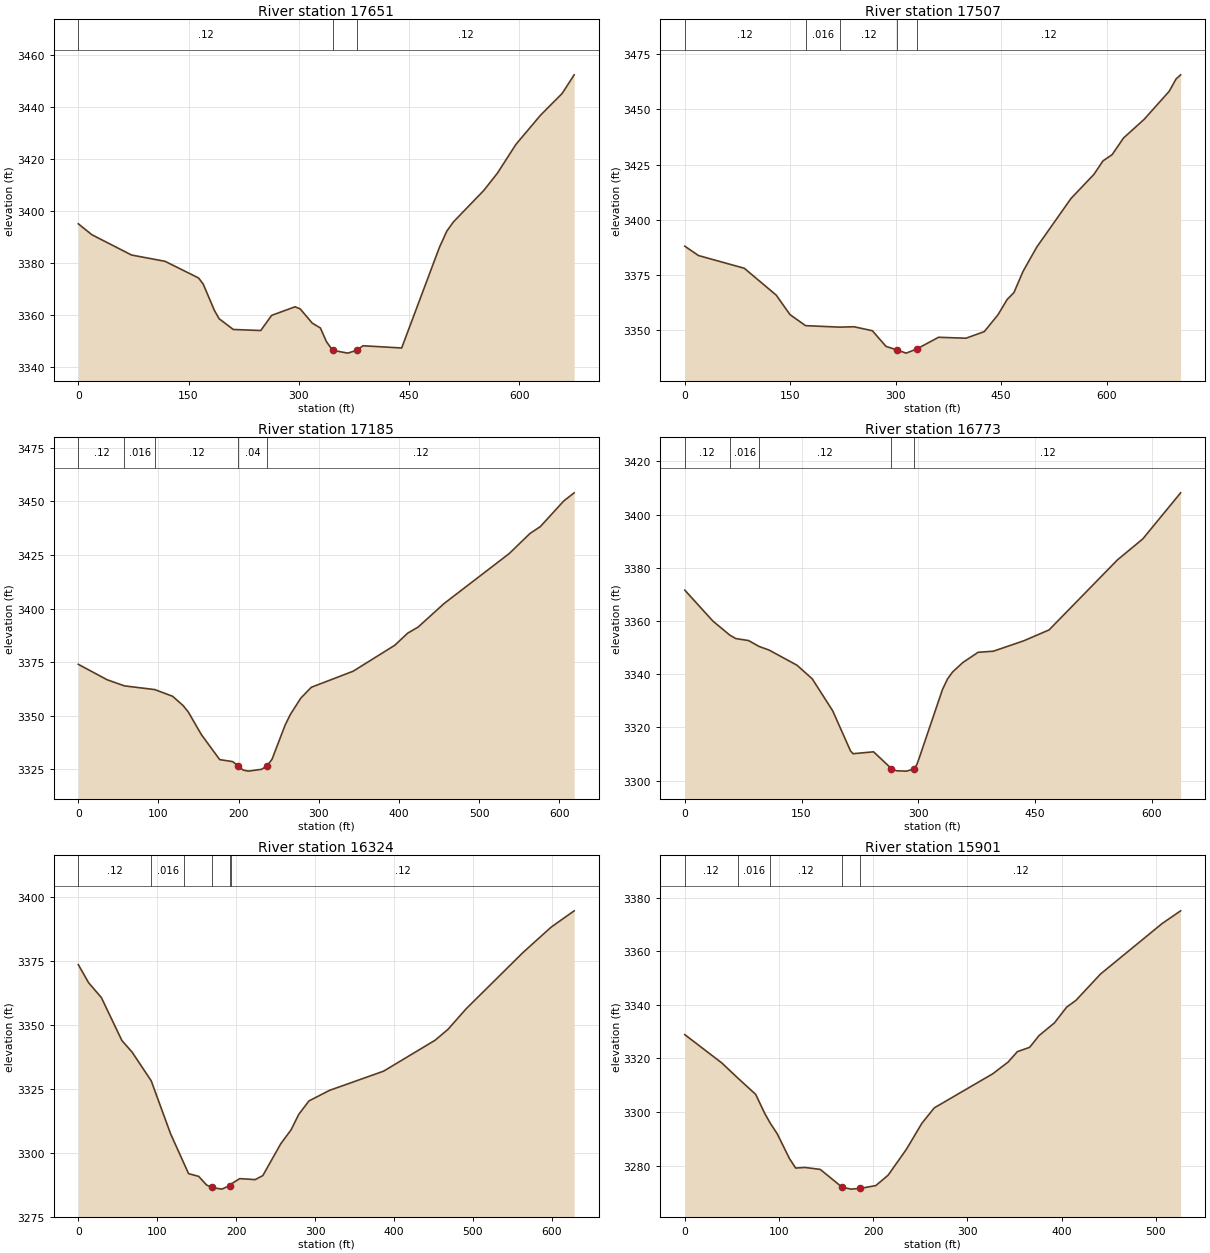
Type RM Length L Ch R = 1 ,17651   ,134.9,143.9,146.7
XS GIS Cut Line= 3
2136601.38231786433261.394846552 2136992.5745026433563.573240756
2137116.72531572433694.751458395
#Sta/Elev= 30
       0 3395.12    18.5 3390.92    72.4 3383.13     118 3380.72   163.6 3374.32
     170 3371.96   185.1 3361.92   191.5 3358.68   210.9 3354.51   248.3 3354.11
   263.1 3359.93   295.1 3363.24   302.1 3362.38   318.4 3356.95   329.5 3355.08
   337.8 3349.78   346.1 3346.51   366.8 3345.42   378.9  3346.5   387.5 3348.25
   440.1  3347.4   491.5 3386.06   501.4 3392.23   510.5 3395.84   551.9 3407.95
   570.5 3414.61   595.7 3425.68   629.1 3436.86   658.6 3445.24   674.9 3452.39
#Mann= 3 , 0 , 0
       0     .12       0   346.1     .04       0   378.9     .12       0
Bank Sta=346.1,378.9
XS Rating Curve= 0 ,0
Exp/Cntr(USF)=0,0
Exp/Cntr=0.3,0.1

Type RM Length L Ch R = 1 ,17507   ,326.8,322.1,321.2
XS GIS Cut Line= 4
     2136560.936      433376.891     2136772.382      433539.381
     2136879.668      433736.245     2137033.825      433885.194
#Sta/Elev= 30
       0 3387.92    19.5 3383.67    84.6  3377.9   130.1 3365.68   149.6 3356.86
  171.74 3351.84  220.21 3351.16   240.6 3351.34   266.7 3349.54   286.2 3342.42
   302.4 3340.74   314.8 3339.36   329.8 3341.22   360.9 3346.56   399.9 3346.13
   425.9 3349.12   445.4 3356.75   458.4  3363.7   468.1 3366.84   481.1  3376.5
   500.6 3387.53   549.3  3409.6   581.8  3420.5   594.8 3426.67   607.8  3429.5
     624 3437.06   653.3 3445.52     689 3458.27   698.7 3463.86   705.2 3465.74
#Mann= 5 ,-1 , 0
       0     .12       0  171.74    .016       0  220.21     .12       0
   302.4     .04       0   329.8     .12       0
Bank Sta=302.4,329.8
XS Rating Curve= 0 ,0
Exp/Cntr=0.3,0.1

Type RM Length L Ch R = 1 ,17185   ,409.7,411.7,408.5
XS GIS Cut Line= 3
     2136444.276      433643.542     2136649.473      433897.694
     2136866.127      434093.516
#Sta/Elev= 30
       0 3373.98    35.9 3366.79   57.51 3363.93   95.47  3362.2   117.6 3359.09
   130.7 3354.77   137.2 3351.77   153.5 3341.23   176.4 3329.54   192.7  3328.6
   199.3 3326.61   205.8 3324.64   212.3 3324.17   228.6 3325.01   235.2  3326.5
   241.7  3329.7     258 3345.62   264.6 3350.62   277.6 3358.21   290.7 3363.27
   342.9 3370.76   394.8 3382.85     411 3388.51     424 3391.36   456.4 3402.33
   537.6 3425.61   563.5 3434.98   576.5 3438.21   605.7 3450.16   618.7 3453.96
#Mann= 5 ,-1 , 0
       0     .12       0   57.51    .016       0   95.47     .12       0
   199.3     .04       0   235.2     .12       0
Bank Sta=199.3,235.2
XS Rating Curve= 0 ,0
Exp/Cntr=0.3,0.1

Type RM Length L Ch R = 1 ,16773   ,452.4,449.7,451.2
XS GIS Cut Line= 3
     2136100.546       433849.78     2136343.241       434154.97
     2136533.854      434312.253
#Sta/Elev= 30
       0 3371.61      36 3360.01   57.83  3354.7    65.5 3353.42    81.9 3352.66
   95.57 3350.43   108.1 3349.12   144.2 3343.39   163.8 3338.26     190 3326.28
     213 3311.15   216.3 3310.15   242.5 3310.87   265.4 3304.58     272 3303.74
   285.1 3303.61   294.9 3304.52   298.2 3306.13   301.4 3308.74     331 3334.24
   337.5 3338.22     344 3340.85   357.2 3344.41   376.8 3348.25   396.4 3348.66
   435.4 3352.56     468 3356.66   555.8 3382.96   588.3 3390.82     637 3408.16
#Mann= 5 ,-1 , 0
       0     .12       0   57.83    .016       0   95.57     .12       0
   265.4     .04       0   294.9     .12       0
Bank Sta=265.4,294.9
XS Rating Curve= 0 ,0
Exp/Cntr=0.3,0.1

Type RM Length L Ch R = 1 ,16324   ,419.8,422.8,425.6
XS GIS Cut Line= 3
     2135765.149      434158.095     2135981.803      434359.125
      2136258.87      434543.489
#Sta/Elev= 30
       0  3373.5      13 3366.46    29.2 3360.64    55.2 3343.86    68.2  3339.3
   92.37 3328.11   116.9 3307.42  134.35 3295.49   139.7 3291.83   152.6 3290.74
   162.4 3287.43   168.9 3286.41   181.9 3285.77   191.6 3287.14     194 3287.84
   204.6 3289.88   224.1 3289.49   233.8 3291.06   256.6 3303.52   269.6 3308.93
   279.3 3314.96   292.3 3320.25   318.4 3324.38   386.9 3331.88   452.2 3343.97
   468.5 3348.22   491.3  3356.2   563.1 3378.12     599 3388.12   628.4 3394.55
#Mann= 6 ,-1 , 0
       0     .12       0   92.37    .016       0  134.35     .12       0
   168.9     .04       0   191.6     .12       0     194     .12       0
Bank Sta=168.9,191.6
XS Rating Curve= 0 ,0
Exp/Cntr=0.3,0.1

Type RM Length L Ch R = 1 ,15901   ,415.8,411.6,405.9
XS GIS Cut Line= 3
     2135562.036      434437.245     2135706.819      434682.023
     2135887.017      434843.472
#Sta/Elev= 30
       0 3328.88    39.2 3318.35   56.37 3312.66    75.2 3306.62      85 3299.41
   90.69 3295.87    98.1 3291.91   111.1 3282.66   117.7 3279.11   127.5 3279.35
   143.8 3278.61     167 3271.97   176.5 3271.26   186.3 3271.55   202.7 3272.57
   215.8 3276.45   235.4 3286.21   251.7 3295.84   264.8 3301.56   326.9 3314.28
   343.2 3318.65     353 3322.54   366.1 3324.15   375.9 3328.49   392.3 3333.24
   405.4 3339.16   415.2 3341.66   441.3 3351.49   506.7 3370.32   526.3 3375.05
#Mann= 5 ,-1 , 0
       0     .12       0   56.37    .016       0   90.69     .12       0
     167     .04       0   186.3     .12       0
Bank Sta=167,186.3
XS Rating Curve= 0 ,0
Exp/Cntr=0.3,0.1

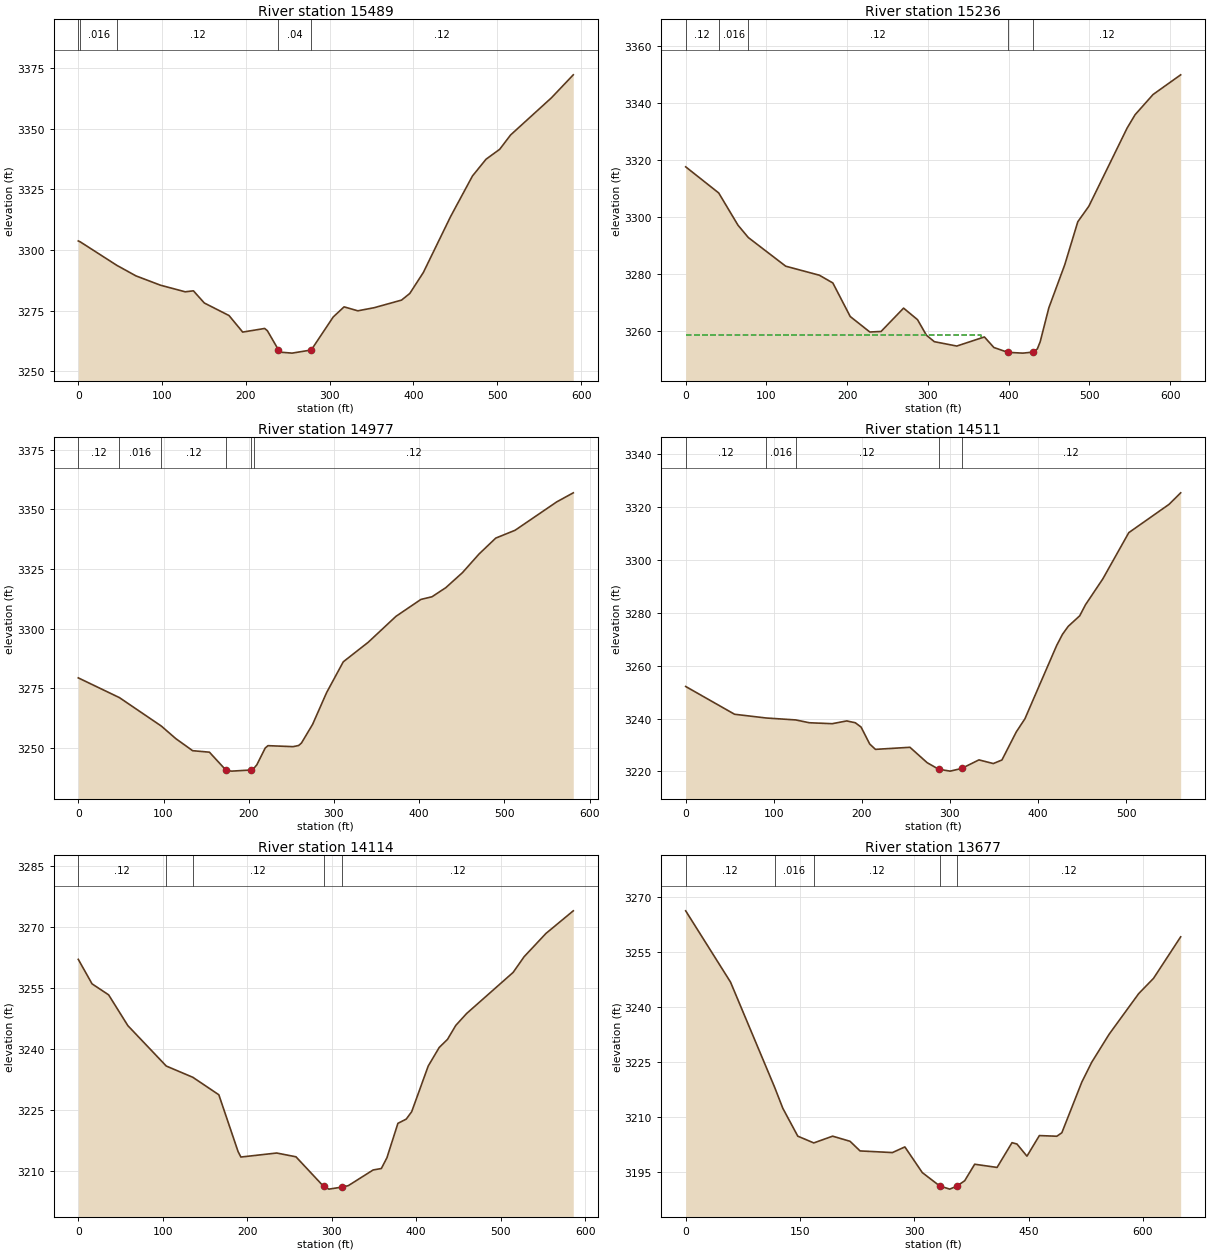
Type RM Length L Ch R = 1 ,15489   ,248.7,253.3,262.1
XS GIS Cut Line= 3
     2135151.643      434692.439     2135433.919      434930.967
      2135583.91      435093.457
#Sta/Elev= 30
       0 3303.73    2.47 3303.33   45.89  3293.7    68.7 3289.34    98.1 3285.48
   127.6 3282.76   137.4 3283.16   150.4 3278.14   179.9 3272.97   196.2 3266.15
   222.4 3267.64   225.7 3266.69   238.7 3258.93     242 3257.84   255.1 3257.47
     278 3258.76   304.2 3272.37   317.2 3276.55   333.6 3274.92   353.2 3276.21
   385.8 3279.34   395.6 3282.08   411.8 3290.74   444.4 3313.86   470.4 3330.52
   486.6 3337.44   502.9 3341.53   515.9 3347.44   564.7 3362.78   590.7 3372.24
#Mann= 5 ,-1 , 0
       0     .12       0    2.47    .016       0   45.89     .12       0
   238.7     .04       0     278     .12       0
Bank Sta=238.7,278
XS Rating Curve= 0 ,0
Exp/Cntr=0.3,0.1

Type RM Length L Ch R = 1 ,15236   ,270.1,259.4,270.3
XS GIS Cut Line= 3
 2135044.2197397434662.3853921372135162.22882411435001.020156077
2135264.84541924 435233.95982703
#Sta/Elev= 30
       0 3317.56    40.9 3308.41    64.8 3297.11    77.6 3292.78   123.9 3282.74
   165.6 3279.58   182.3 3276.86   203.8 3265.11   228.1 3259.68     242 3259.87
   269.9 3268.05   287.2 3263.99   298.2 3258.55     308 3256.29   335.8 3254.76
     370 3257.95   381.7 3254.26     399 3252.55   417.5 3252.28   429.7 3252.62
   435.5 3253.72   439.1 3256.26   449.8 3268.14   469.5 3283.23   485.7 3298.32
   499.4 3303.77   546.8 3331.16   556.6  3335.8   578.9  3342.9   613.1  3349.8
#Mann= 5 ,-1 , 0
       0     .12       0    40.9    .016       0    77.6     .12       0
     399     .04       0   429.7     .12       0
#XS Ineff= 2 , 0
          365.98  3258.7
Permanent Ineff=
       F       F
Bank Sta=399,429.7
XS Rating Curve= 0 ,0
Exp/Cntr=0.3,0.1

Type RM Length L Ch R = 1 ,14977   ,458.4,465.4,461.5
XS GIS Cut Line= 3
      2134864.16      434814.307     2135014.151      435083.041
     2135126.645      435331.985
#Sta/Elev= 30
       0 3279.33   48.31 3271.04   97.31 3259.15   114.6  3253.8   134.2 3248.78
   153.9 3248.16   173.5 3240.55   180.1 3240.21     203 3240.69   206.3 3241.52
   209.5 3242.84   219.4 3249.92   222.6 3250.89   252.1 3250.48   258.6 3250.96
   261.9 3251.99     275 3259.84   291.4 3273.14     311 3286.08   340.3 3294.28
   372.8 3305.14   402.1 3312.24   415.1 3313.36   431.3 3317.17   450.8 3323.46
   470.4 3331.32   489.9 3337.96   512.6 3341.25   561.4 3353.14   580.9 3356.96
#Mann= 6 ,-1 , 0
       0     .12       0   48.31    .016       0   97.31     .12       0
   173.5     .04       0     203     .12       0   206.3     .12       0
Bank Sta=173.5,203
XS Rating Curve= 0 ,0
Exp/Cntr=0.3,0.1

Type RM Length L Ch R = 1 ,14511   ,382.9,397.5,404.3
XS GIS Cut Line= 3
     2134407.937      434908.051     2134591.259      435239.282
     2134681.879      435398.648
#Sta/Elev= 30
       0 3252.14    55.5 3241.62   91.24 3240.21     125 3239.47   140.3 3238.41
   166.4 3238.05   182.8  3239.1   192.6  3238.4   199.1 3236.77   208.9 3230.36
   215.4 3228.33   254.6 3229.11   274.1 3223.29   287.2  3220.8   300.2 3220.09
   313.3  3221.1   332.9 3224.35   349.2 3222.96     359  3224.3   375.3 3234.94
   385.1 3239.91   421.1 3267.64   427.7 3271.87   434.2 3274.89   447.3  3278.9
   453.9 3283.11   473.5 3292.86     503 3310.38   548.8 3321.12   561.9 3325.46
#Mann= 5 ,-1 , 0
       0     .12       0   91.24    .016       0     125     .12       0
   287.2     .04       0   313.3     .12       0
Bank Sta=287.2,313.3
XS Rating Curve= 0 ,0
Exp/Cntr=0.3,0.1

Type RM Length L Ch R = 1 ,14114   ,433.7,437.2,437.9
XS GIS Cut Line= 3
     2134312.109      434890.344      2134156.91      435305.945
     2134142.327      435447.603
#Sta/Elev= 30
       0 3262.13    16.3  3256.1    35.9  3253.4    58.7 3245.81  104.12 3235.87
  135.65 3233.09   166.4 3228.79   189.2 3214.79   192.5 3213.46   234.9 3214.45
   257.7 3213.52   290.3 3206.26   296.7 3205.56   311.7 3206.04   319.7 3206.42
     349 3210.27   358.8 3210.64   365.4 3213.29   378.4 3221.76   388.2 3222.79
   394.7 3224.62   414.3 3235.88   427.3 3240.44   437.1 3242.43   446.9 3245.87
   459.8 3248.81   514.8 3258.92   527.8 3262.78   553.7 3268.52     586 3274.08
#Mann= 5 ,-1 , 0
       0     .12       0  104.12    .016       0  135.65     .12       0
   290.3     .04       0   311.7     .12       0
Bank Sta=290.3,311.7
XS Rating Curve= 0 ,0
Exp/Cntr=0.3,0.1

Type RM Length L Ch R = 1 ,13677   ,391.5,395.7,400.6
XS GIS Cut Line= 3
     2133970.698      434753.186     2133700.652      435227.553
     2133649.215      435317.568
#Sta/Elev= 30
       0 3266.26    58.8 3246.86   116.6 3218.25   127.5 3212.45   147.1 3204.87
   168.1 3203.03   192.8 3204.87   215.7 3203.47   228.8 3200.85   271.3  3200.4
   287.6 3201.94   310.5 3194.94   333.4  3191.3   346.5 3190.44   355.8 3191.26
   366.1 3192.72   379.2 3197.22   408.6 3196.35   428.2  3203.1   434.7 3202.73
   447.8 3199.42   464.1 3205.03     487 3204.85   493.6  3205.8   519.7 3219.56
   532.8 3225.01   555.6 3232.63   594.4  3243.7   613.9 3247.87   649.5 3259.17
#Mann= 5 ,-1 , 0
       0     .12       0   116.6    .016       0   168.1     .12       0
   333.4     .04       0   355.8     .12       0
Bank Sta=333.4,355.8
XS Rating Curve= 0 ,0
Exp/Cntr=0.3,0.1