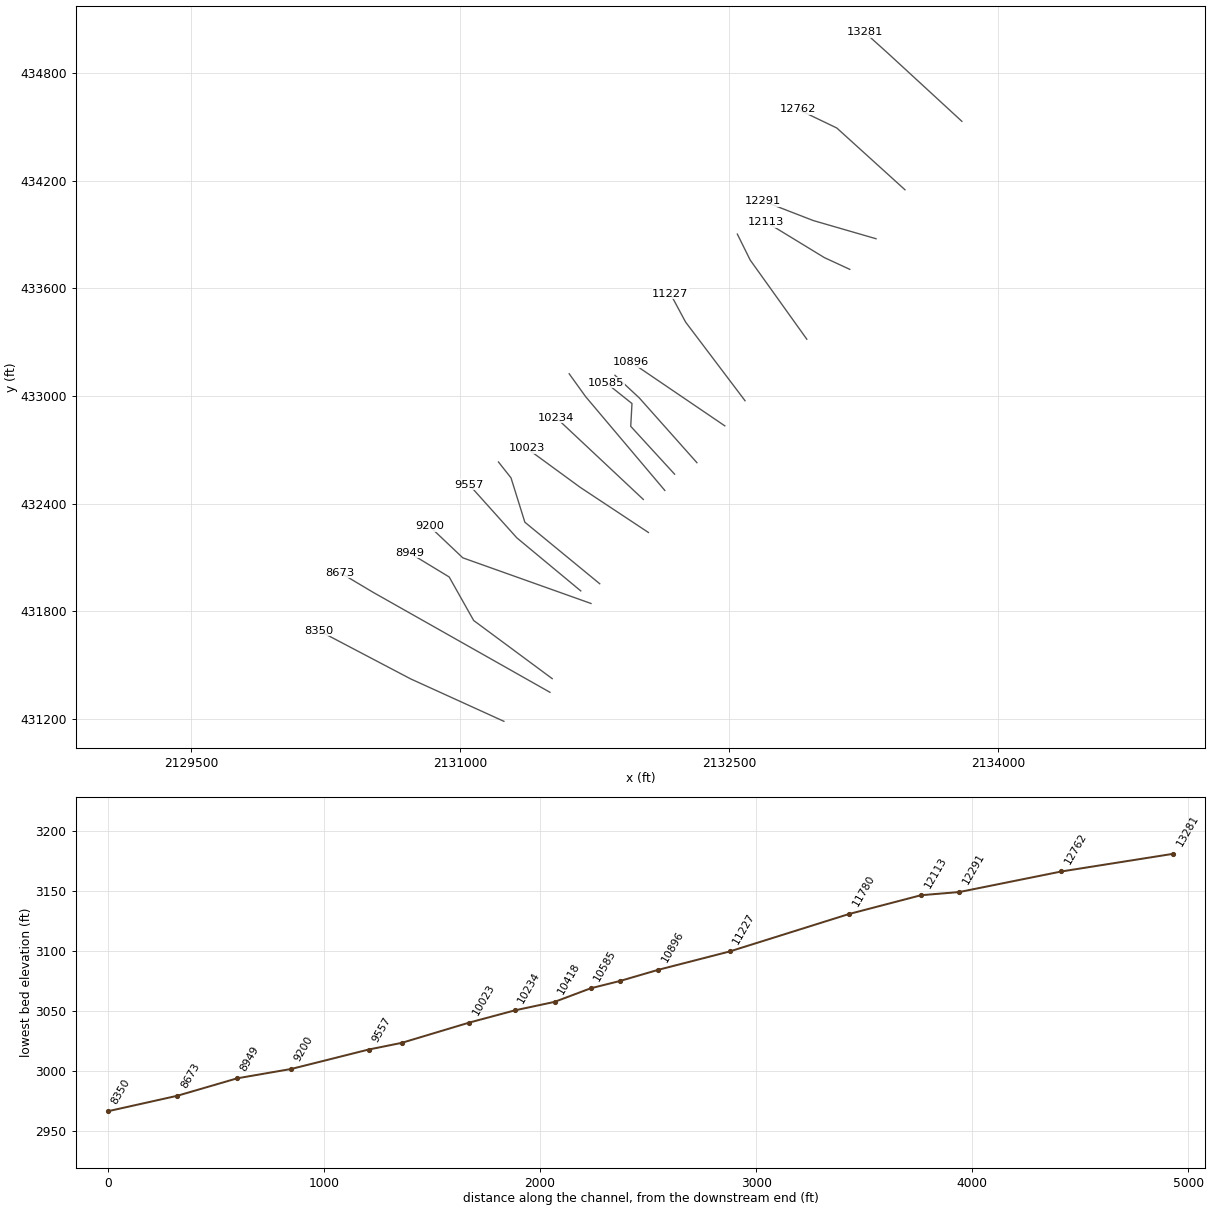
HEC-RAS study ROCKYRN.prj: ROCKYRN

--- ROCKYRN.g01 (geometry) --- (continued)

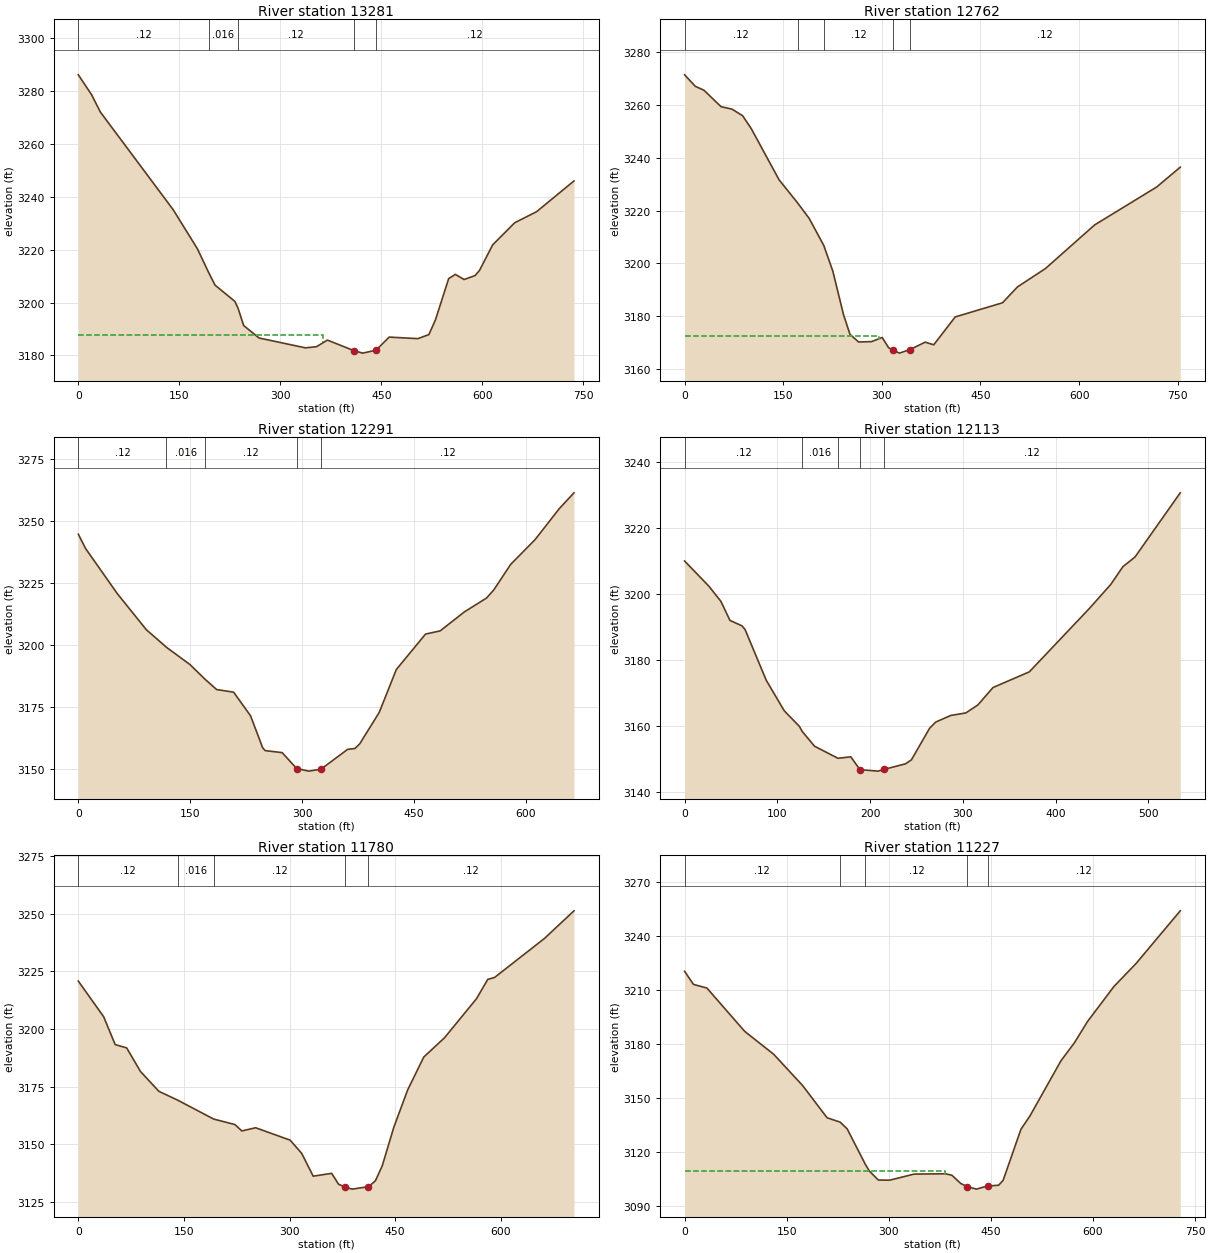
Type RM Length L Ch R = 1 ,13281   ,518.6,518.9,520.6
XS GIS Cut Line= 3
     2133796.383       434531.72     2133382.026      434913.214
     2133253.433      435028.948
#Sta/Elev= 30
       0 3286.15    19.6 3278.67    32.8 3272.05   140.8 3235.16   176.8 3220.38
   193.8 3211.25     203 3206.61   232.5 3200.45  237.41 3197.74   245.6 3191.31
   268.5 3186.59   337.3 3182.87   353.7 3183.29     370  3185.8   409.3 3181.82
   422.4 3180.87   442.1 3181.96   461.7 3186.93   504.3 3186.35   520.7 3187.88
   530.5 3193.48   550.1 3209.07     560 3210.66     573 3208.71   589.4 3210.22
   595.9 3212.16   615.5 3221.84   648.1 3230.18   680.7 3234.38   736.2 3246.01
#Mann= 5 ,-1 , 0
       0     .12       0   193.8    .016       0  237.41     .12       0
   409.3     .04       0   442.1     .12       0
#XS Ineff= 2 , 0
          364.12 3187.62
Permanent Ineff=
       F       F
Bank Sta=409.3,442.1
XS Rating Curve= 0 ,0
Exp/Cntr=0.3,0.1

Type RM Length L Ch R = 1 ,12762   ,465.4,471.4,477.7
XS GIS Cut Line= 3
     2133479.186      434150.227     2133099.121      434494.571
     2132881.941      434598.874
#Sta/Elev= 30
       0 3271.29    16.3 3266.94    29.4 3265.47    55.5 3259.24    71.9 3258.34
    88.2 3255.84   101.3 3250.99   143.7 3231.61  171.86 3222.88   189.5 3217.01
  211.72 3206.78   225.4 3197.12   241.7 3180.64   251.5 3173.21   264.6 3170.32
   284.2 3170.44   300.5 3172.01   310.3 3168.15   316.9 3167.25   326.7  3166.1
     343 3167.47   365.9 3170.24   378.9 3169.25   411.6 3179.78   483.5 3185.13
   506.3 3191.14   548.7 3198.05   623.6 3214.55     718  3228.9   753.8 3236.38
#Mann= 5 ,-1 , 0
       0     .12       0  171.86    .016       0  211.72     .12       0
   316.9     .04       0     343     .12       0
#XS Ineff= 2 , 0
          295.65 3172.53
Permanent Ineff=
       F       F
Bank Sta=316.9,343
XS Rating Curve= 0 ,0
Exp/Cntr=0.3,0.1

Type RM Length L Ch R = 1 ,12291   ,178.2,177.6,171.7
XS GIS Cut Line= 3
      2133317.73      433877.323      2132967.67      433978.769
     2132687.622      434087.359
#Sta/Elev= 30
       0  3244.5     9.8 3238.71    52.1 3220.62    91.1 3206.04  118.26  3198.9
   149.7 3191.97  169.79 3186.08   185.5 3181.87   208.3 3180.81     231  3171.3
   247.3 3158.37   250.6 3157.26   273.4 3156.44   292.9 3150.02   309.1 3148.98
   325.4 3149.74   361.2 3157.76     371  3158.1   377.5 3160.01   403.6 3172.65
   426.5 3189.93   465.7 3204.24   485.3 3205.52   517.9  3213.2   547.3 3218.72
   557.1 3221.97   579.9 3232.34   612.6 3242.31   645.2 3254.85   664.8 3261.19
#Mann= 5 ,-1 , 0
       0     .12       0  118.26    .016       0  169.79     .12       0
   292.9     .04       0   325.4     .12       0
Bank Sta=292.9,325.4
XS Rating Curve= 0 ,0
Exp/Cntr=0.3,0.1

Type RM Length L Ch R = 1 ,12113   ,337.5,332.9,328.3
XS GIS Cut Line= 4
     2133171.502      433706.604     2133029.571      433772.214
     2132926.471      433835.145      2132706.88      433969.042
#Sta/Elev= 30
       0 3210.07    26.1 3202.46    39.1 3197.85    48.9 3192.05    61.9  3190.4
    65.2 3189.28      88  3173.9   107.5  3164.6   123.8 3159.89  126.74 3158.37
   140.1 3153.88  165.36 3150.21   179.2 3150.66     189 3146.76   208.6 3146.32
   215.1 3146.86     238 3148.52   244.5 3149.74   264.1 3159.31   270.6 3161.19
   286.9 3163.21   303.2 3163.98   316.2 3166.41   332.5 3171.69   371.6 3176.44
   436.7 3195.78   459.5    3203   472.5 3208.36   485.5 3211.27   534.3 3230.76
#Mann= 5 ,-1 , 0
       0     .12       0  126.74    .016       0  165.36     .12       0
     189     .04       0   215.1     .12       0
Bank Sta=189,215.1
XS Rating Curve= 0 ,0
Exp/Cntr=0.3,0.1

Type RM Length L Ch R = 1 ,11780   ,549.8,552.7,551.6
XS GIS Cut Line= 3
      2132931.95      433317.228     2132616.182      433758.731
     2132544.741      433903.042
#Sta/Elev= 30
       0 3220.79      36 3205.35    52.3 3193.31    68.7 3191.83    88.3 3181.62
   114.4 3173.04  141.37 3169.17  192.15 3161.02   222.4 3158.63   232.2 3155.86
   251.8 3157.26   300.8 3151.87   317.2 3146.15   333.5 3136.27   359.7  3137.5
   369.5 3132.79   379.3  3131.5   389.1 3130.66     412 3131.73   421.8 3134.23
   431.6  3140.8     448 3157.48   467.6  3173.6   490.5 3187.88   519.9 3196.22
   565.4 3213.16   581.4 3221.53   591.1 3222.37     662  3239.3   703.8 3251.24
#Mann= 5 ,-1 , 0
       0     .12       0  141.37    .016       0  192.15     .12       0
   379.3     .04       0     412     .12       0
Bank Sta=379.3,412
XS Rating Curve= 0 ,0
Exp/Cntr=0.3,0.1

Type RM Length L Ch R = 1 ,11227   ,325.2,331.5,335.1
XS GIS Cut Line= 3
     2132587.605      432974.312      2132256.12      433412.958
      2132171.82      433570.128
#Sta/Elev= 30
       0 3220.23    13.1 3212.96    32.7 3210.98    88.4  3186.9   130.9 3174.23
   173.4 3156.87   209.4 3138.99  228.54 3136.58   238.9 3132.83  265.56 3113.17
   271.6 3109.38   284.7 3104.46   301.1 3104.37   337.1 3107.74   382.9 3107.94
   392.7 3107.13   405.8 3102.53   415.6 3100.79   428.7 3099.42   445.1 3101.16
   461.4 3101.58     468 3104.32   494.2 3132.65   507.3 3139.96     553 3170.65
   572.5 3180.47     592 3192.41   630.9 3211.87   663.3 3224.57   728.2 3253.79
#Mann= 5 ,-1 , 0
       0     .12       0  228.54    .016       0  265.56     .12       0
   415.6     .04       0   445.1     .12       0
#XS Ineff= 2 , 0
          382.61 3109.28
Permanent Ineff=
       F       F
Bank Sta=415.6,445.1
XS Rating Curve= 0 ,0
Exp/Cntr=0.3,0.1

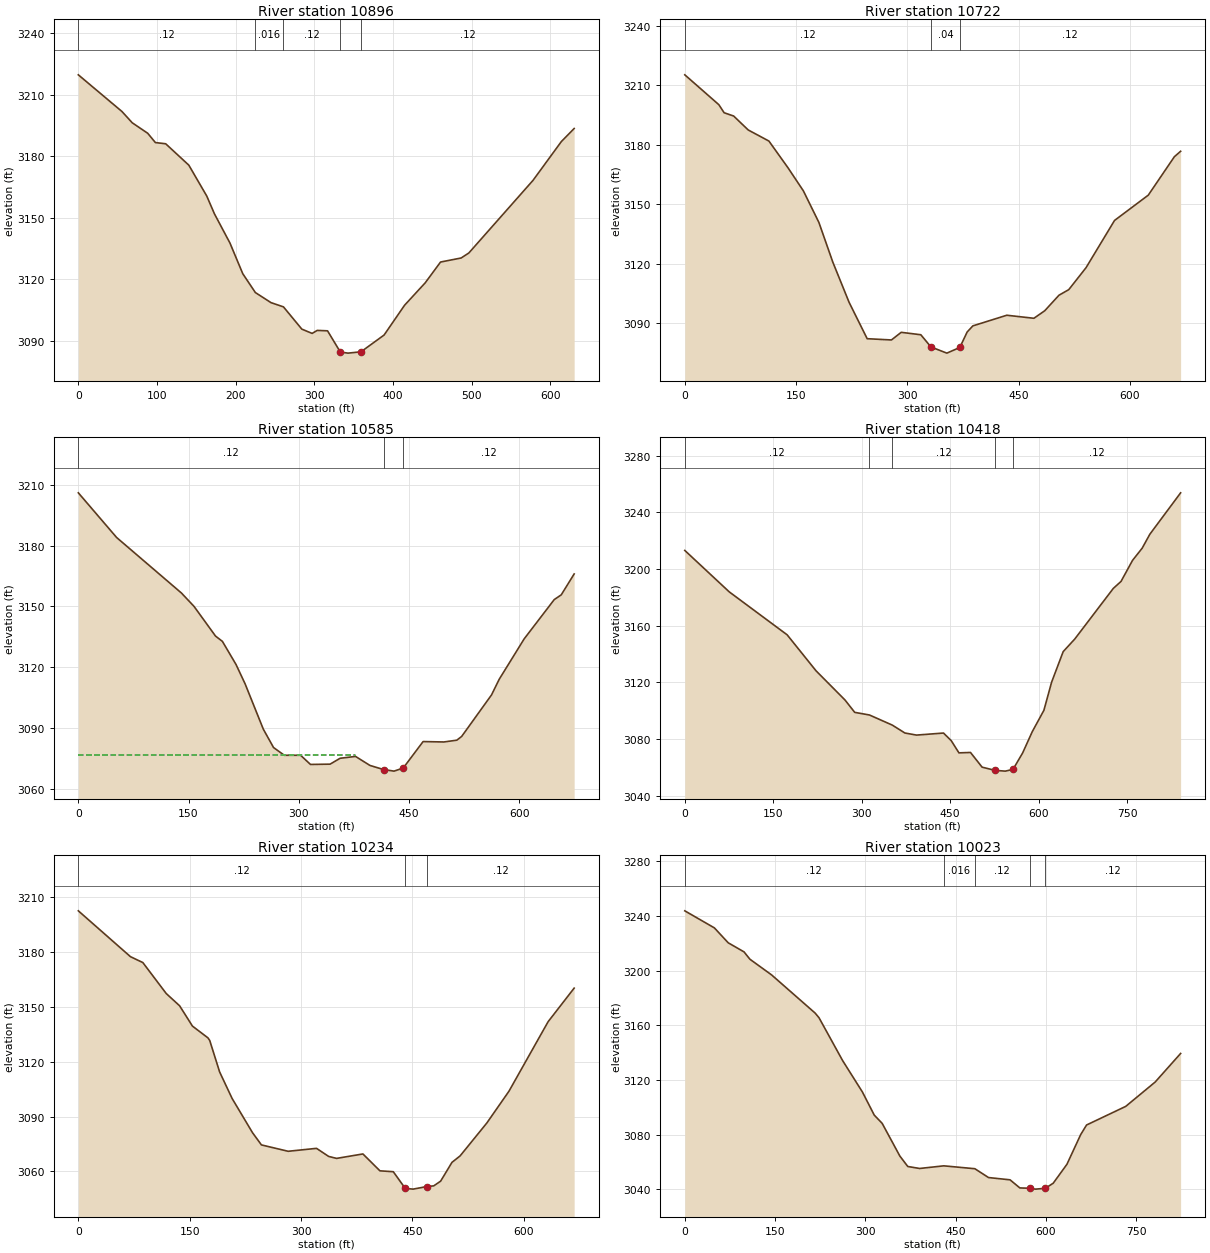
Type RM Length L Ch R = 1 ,10896   ,178.9,174.2,170.2
XS GIS Cut Line= 2
     2132474.729      432834.288     2131953.212      433188.634
#Sta/Elev= 30
       0 3219.59    55.5 3201.72    68.6 3196.22    88.2 3191.14      98  3186.6
   111.1 3186.01   140.5  3175.6   163.3 3160.57   173.1 3151.88   192.8 3137.68
   209.1 3122.74  225.13 3113.56     245 3108.65  260.84 3106.59   284.2 3095.75
   297.3 3093.66   303.8 3095.13   316.9 3094.92   333.2 3084.57     343 3084.06
   359.4  3084.7   388.8 3092.87   414.9  3107.4     441 3118.25   460.6 3128.42
   486.8 3130.39   496.6 3132.84   578.2  3168.2   614.2 3187.08   630.5 3193.44
#Mann= 5 ,-1 , 0
       0     .12       0  225.13    .016       0  260.84     .12       0
   333.2     .04       0   359.4     .12       0
Bank Sta=333.2,359.4
XS Rating Curve= 0 ,0
Exp/Cntr=0.3,0.1

Type RM Length L Ch R = 1 ,10722   ,155.3,136.8,124.8
XS GIS Cut Line= 3
2132319.35049922 432628.928440082131998.43235964432989.668538587
2131862.56920566433116.161819881
#Sta/Elev= 30
       0  3215.2    45.9 3200.15      53 3196.09    65.9 3194.42    85.5  3187.4
   113.4 3181.81     139 3168.41   159.9 3156.68   180.8 3140.78   199.6 3120.74
   221.5 3100.52   245.9 3082.16   278.6 3081.53   291.8 3085.38   318.2 3084.16
   331.9    3078   353.3 3074.89   370.8 3077.74   380.7 3085.54   388.4 3088.63
   434.1 3093.99   470.7 3092.46   485.3 3096.26   504.5 3104.09   517.7  3106.9
     541 3117.98   579.4 3141.78   624.9 3154.54   660.1 3173.92   668.5 3176.66
#Mann= 3 , 0 , 0
       0     .12       0   331.9     .04       0   370.8     .12       0
Bank Sta=331.9,370.8
XS Rating Curve= 0 ,0
Exp/Cntr(USF)=0,0
Exp/Cntr=0.3,0.1

Type RM Length L Ch R = 1 ,10585   ,160.9,167.1,182.6
XS GIS Cut Line= 4
2132194.99657177432564.8487172582131950.42880905432831.524300341
2131957.33750291432958.644267406 2131812.2549318433074.710324292
#Sta/Elev= 30
       0 3206.09    52.1 3184.05   140.4 3156.62   157.5 3150.04   186.8 3135.37
   196.1 3132.78   214.7 3121.34     227 3111.82   251.8 3089.45   265.7 3080.39
   280.4 3076.56   302.6 3076.55     316 3072.04   342.7 3072.18   356.3 3075.08
   377.3    3076     397 3071.54   415.53069.527   429.7 3068.74   442.2 3070.25
   469.3 3083.33   497.6 3083.13   515.2 3084.02   521.8 3085.87   562.4 3106.34
   572.9 3114.08   606.9 3134.03   647.8  3153.4   657.3 3155.73   674.9 3166.05
#Mann= 3 , 0 , 0
       0     .12       0   415.5     .04       0   442.2     .12       0
#XS Ineff= 2 , 0
           376.5 3076.46
Permanent Ineff=
       F       F
Bank Sta=415.5,442.2
XS Rating Curve= 0 ,0
Exp/Cntr(USF)=0,0
Exp/Cntr=0.3,0.1

Type RM Length L Ch R = 1 ,10418   ,183.5,184.2,187.1
XS GIS Cut Line= 3
     2132140.386      432474.227     2131698.883      432997.173
     2131607.439      433124.338
#Sta/Elev= 30
       0 3213.06    75.3 3183.86   173.6 3153.54   222.7 3128.12   271.8 3107.54
   288.2 3098.86  313.27 3096.99  351.93 3089.88   373.3  3084.3     393 3082.82
   438.8 3084.27   451.9 3078.92     465 3070.29   484.6 3070.57   504.3  3060.2
   526.3 3057.94   543.6 3057.41   556.7 3058.63   573.1 3070.28   589.4 3085.26
   609.1 3100.31   622.2 3120.18   641.8 3141.68   661.5  3150.6   726.8 3186.26
   739.9  3191.2   759.4 3206.01   775.8 3214.65   788.8 3224.48     841 3253.68
#Mann= 5 ,-1 , 0
       0     .12       0  313.27    .016       0  351.93     .12       0
   526.3     .04       0   556.7     .12       0
Bank Sta=526.3,556.7
XS Rating Curve= 0 ,0
Exp/Cntr=0.3,0.1

Type RM Length L Ch R = 1 ,10234   ,208.8,210.4,212
XS GIS Cut Line= 2
2132020.66056278432423.9890734292131533.54552229432880.777885719
#Sta/Elev= 30
       0 3202.64    70.2 3177.55    86.9 3174.32   118.4 3157.37   136.4 3150.67
   153.7 3139.55   174.6  3133.1     177 3131.66   190.3 3114.47   207.1 3099.95
   234.6 3081.21   246.6 3074.52   282.6 3071.03   320.8 3072.64   337.1 3068.23
   347.8 3067.14   383.3 3069.57   406.2 3060.34   424.2 3059.85   440.33050.736
   450.8 3050.32   469.4 3051.72   478.7 3052.11     488  3054.7   503.2 3064.95
   514.2 3068.51   550.2 3086.52     580 3103.91   632.7 3141.94   667.8 3160.33
#Mann= 3 , 0 , 0
       0     .12       0   440.3     .04       0   469.4     .12       0
Bank Sta=440.3,469.4
XS Rating Curve= 0 ,0
Exp/Cntr(USF)=0,0
Exp/Cntr=0.3,0.1

Type RM Length L Ch R = 1 ,10023   ,323,313,298.8
XS GIS Cut Line= 3
     2132048.942      432239.901     2131668.878      432491.373
     2131371.684      432708.553
#Sta/Elev= 30
       0 3243.65    49.2 3231.16    72.1 3220.28    98.4 3213.63   108.2 3208.26
   144.3 3196.76   216.4 3168.94     223 3165.47   262.3 3134.09   295.1 3111.18
   314.8 3094.26   327.9 3088.26   357.4 3064.28   370.5  3056.7   390.2 3055.25
  430.24 3057.18  481.95 3055.07   504.6 3048.62   540.4 3046.95   556.7 3041.02
     573  3040.8   582.8 3040.15     599 3040.75   612.1 3044.47   634.9  3058.3
   657.7 3079.97   667.5 3087.03   732.6 3100.65   781.5 3118.45   823.8 3139.35
#Mann= 5 ,-1 , 0
       0     .12       0  430.24    .016       0  481.95     .12       0
     573     .04       0     599     .12       0
Bank Sta=573,599
XS Rating Curve= 0 ,0
Exp/Cntr=0.3,0.1

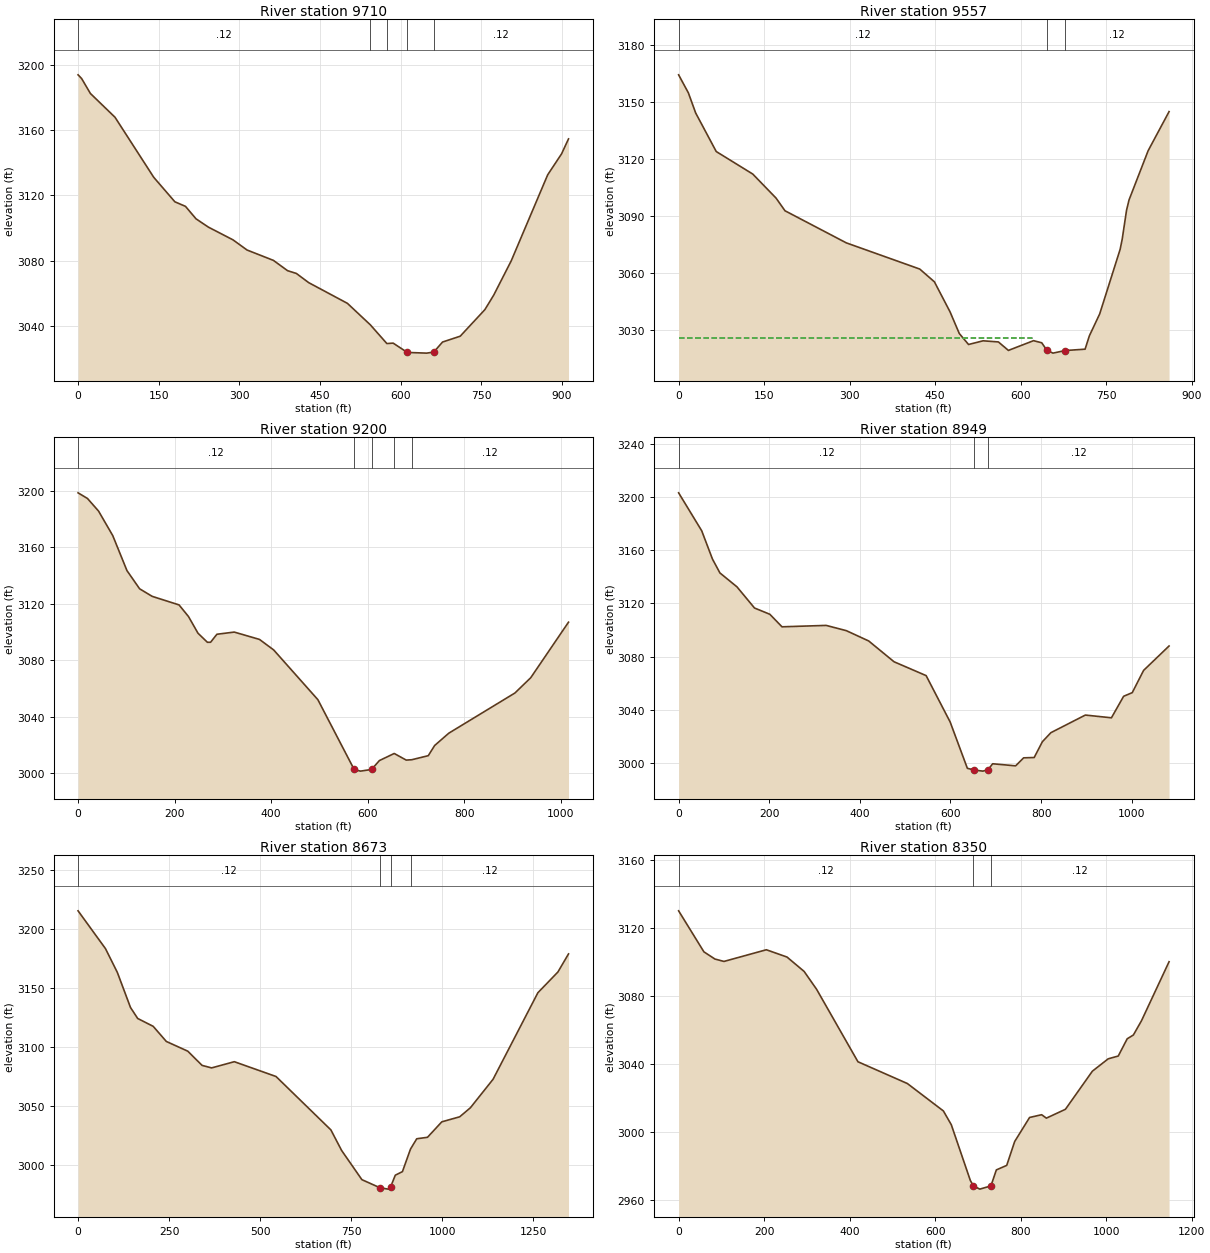
Type RM Length L Ch R = 1 ,9710    ,149.8,153.1,161.3
XS GIS Cut Line= 4
     2131777.468      431954.138     2131360.254      432297.054
     2131283.098      432544.239     2131213.086      432632.825
#Sta/Elev= 30
       0 3193.82     6.6 3191.56    22.9  3182.4    68.7 3167.81   140.7 3131.01
     180 3115.99   199.7  3113.2   219.3 3105.56   242.2 3100.49     288 3092.68
   314.2 3086.43   363.3 3080.07   389.5 3073.77   405.9 3072.07   428.8 3066.44
   500.8 3053.75  543.24 3040.64  574.18  3029.1   585.9 3029.35   612.2 3023.65
   648.2 3023.23   661.3 3023.87   677.7 3030.03   710.5  3033.6   756.4 3049.89
   772.8 3058.76   805.4 3079.81   873.2 3132.54     899 3145.39   911.9 3154.55
#Mann= 5 ,-1 , 0
       0     .12       0  543.24    .016       0  574.18     .12       0
   612.2     .04       0   661.3     .12       0
Bank Sta=612.2,661.3
XS Rating Curve= 0 ,0
Exp/Cntr=0.3,0.1

Type RM Length L Ch R = 1 ,9557    ,352.3,357.4,366.6
XS GIS Cut Line= 3
2131671.90893846431914.1293617852131315.57575709432209.810086753
2131050.22126032432505.490811721
#Sta/Elev= 30
       0 3164.32    17.1 3154.84    29.9 3144.23      66  3123.9   130.1 3112.02
   170.9 3099.37   186.6 3092.68   294.2 3075.76     423 3061.96   448.7 3055.23
   476.1 3039.43   492.3 3028.01   508.6 3022.21   534.1 3024.15   560.9 3023.56
   578.5 3019.09   622.6 3024.23     637  3023.1  645.87 3019.19   656.6 3017.66
   678.2 3019.03     713 3019.74   720.5 3026.78   738.6 3038.31   774.5 3072.37
   778.1 3077.69   785.7 3092.93   790.1  3098.4   823.6 3124.33   860.3 3144.93
#Mann= 3 , 0 , 0
       0     .12       0  645.87     .04       0   678.2     .12       0
#XS Ineff= 2 , 0
          620.27 3025.47
Permanent Ineff=
       F       F
Bank Sta=645.87,678.2
XS Rating Curve= 0 ,0
Exp/Cntr(USF)=0,0
Exp/Cntr=0.3,0.1

Type RM Length L Ch R = 1 ,9200    ,264.7,250.4,241.6
XS GIS Cut Line= 3
     2131728.888       431844.12      2131014.48      432098.449
     2130827.306      432275.622
#Sta/Elev= 30
       0 3198.36    19.6 3194.34    42.5 3185.42    71.9 3168.09   101.3 3143.35
   127.5 3130.48   153.6 3125.12   209.2 3119.08   228.8 3110.85   248.4 3099.09
     268 3092.62   274.6 3092.67   287.6 3098.31   323.6 3099.86   375.9 3094.66
   405.3 3087.22   496.8 3052.06     572 3002.68   585.1  3001.5     608 3002.67
   624.3 3008.97  655.02 3013.98   679.9  3009.3   691.4 3009.56   725.6 3012.44
   738.7  3019.6   768.1 3028.34   905.1 3056.77   937.8 3067.56  1016.1 3106.86
#Mann= 5 ,-1 , 0
       0     .12       0     572     .04       0     608     .12       0
  655.02    .016       0   691.4     .12       0
Bank Sta=572,608
XS Rating Curve= 0 ,0
Exp/Cntr=0.3,0.1

Type RM Length L Ch R = 1 ,8949    ,262.6,276.4,278.5
XS GIS Cut Line= 4
 2131512.6962404431425.1189320292131074.86132074431749.230495937
2130938.39329383431991.840321552 2130716.6327501432126.412959198
#Sta/Elev= 30
       0 3203.32      51 3174.72    74.7 3153.43    91.2 3142.96   128.7 3132.53
   167.5 3116.56   201.4 3111.83   228.2 3102.39   325.7 3103.45   370.3 3099.47
   419.5 3091.74   475.5 3076.06   546.3 3065.63   599.3 3030.72   637.3 2995.82
   652.3 2994.49   671.5 2993.68   682.5 2994.67   693.2 2999.22   743.8 2997.66
   761.5 3003.69   784.8 3003.93   802.9 3015.84   821.7 3022.65   897.7 3035.91
   955.3 3033.85   982.2 3050.05  1001.3 3052.82  1026.3 3069.56  1082.5 3087.95
#Mann= 3 , 0 , 0
       0     .12       0   652.3     .04       0   682.5     .12       0
Bank Sta=652.3,682.5
XS Rating Curve= 0 ,0
Exp/Cntr(USF)=0,0
Exp/Cntr=0.3,0.1

Type RM Length L Ch R = 1 ,8673    ,321.8,322.7,323.1
XS GIS Cut Line= 3
     2131500.313      431348.903     2130514.254      431906.317
     2130330.801      432015.683
#Sta/Elev= 30
       0 3215.45    75.3 3183.34     108 3163.04     144 3133.35   163.7 3124.05
   206.2 3117.39   242.3 3104.54   301.2 3096.28   340.5 3084.21   366.7 3082.09
   428.9 3087.35   543.4 3074.79     694 3029.45   723.5 3011.98   779.1 2987.21
   828.2  2980.4   851.2 2979.16   857.7 2980.85   870.8 2990.98   890.4 2994.01
  912.55 3013.16   929.7 3021.91   959.2 3023.16   998.5  3036.3  1047.6 3040.57
    1077 3048.25  1139.2 3072.42  1262.2  3145.9  1317.2  3163.5  1346.3 3178.86
#Mann= 4 ,-1 , 0
       0     .12       0   828.2     .04       0   857.7    .016       0
  912.55     .12       0
Bank Sta=828.2,857.7
XS Rating Curve= 0 ,0
Exp/Cntr=0.3,0.1

Type RM Length L Ch R = 1 ,8350    ,613.3,629.5,639.3
XS GIS Cut Line= 3
2131243.41395656431187.1766217572130723.41690234431423.775281427
 2130213.8197892 431691.57376435
#Sta/Elev= 30
       0  3129.9    59.2 3105.76      85 3101.54     106 3100.13   205.2    3107
   253.5 3102.71   293.5 3094.27   322.8 3083.71   419.4 3041.12     535 3028.31
   619.2 3012.19   637.7  3004.1   682.3 2971.26   689.5 2968.11   704.4  2966.2
   730.4  2968.1   743.1 2977.51   767.3 2980.16     786 2994.23   820.8 3008.35
     849 3009.97   860.1 3007.96   904.6 3013.15   967.6 3035.56  1004.6 3042.84
  1028.2  3044.5  1049.1 3054.63  1063.5 3056.85  1082.5 3065.24    1147 3099.96
#Mann= 3 , 0 , 0
       0     .12       0   689.5     .04       0   730.4     .12       0
Bank Sta=689.5,730.4
XS Rating Curve= 0 ,0
Exp/Cntr(USF)=0,0
Exp/Cntr=0.3,0.1