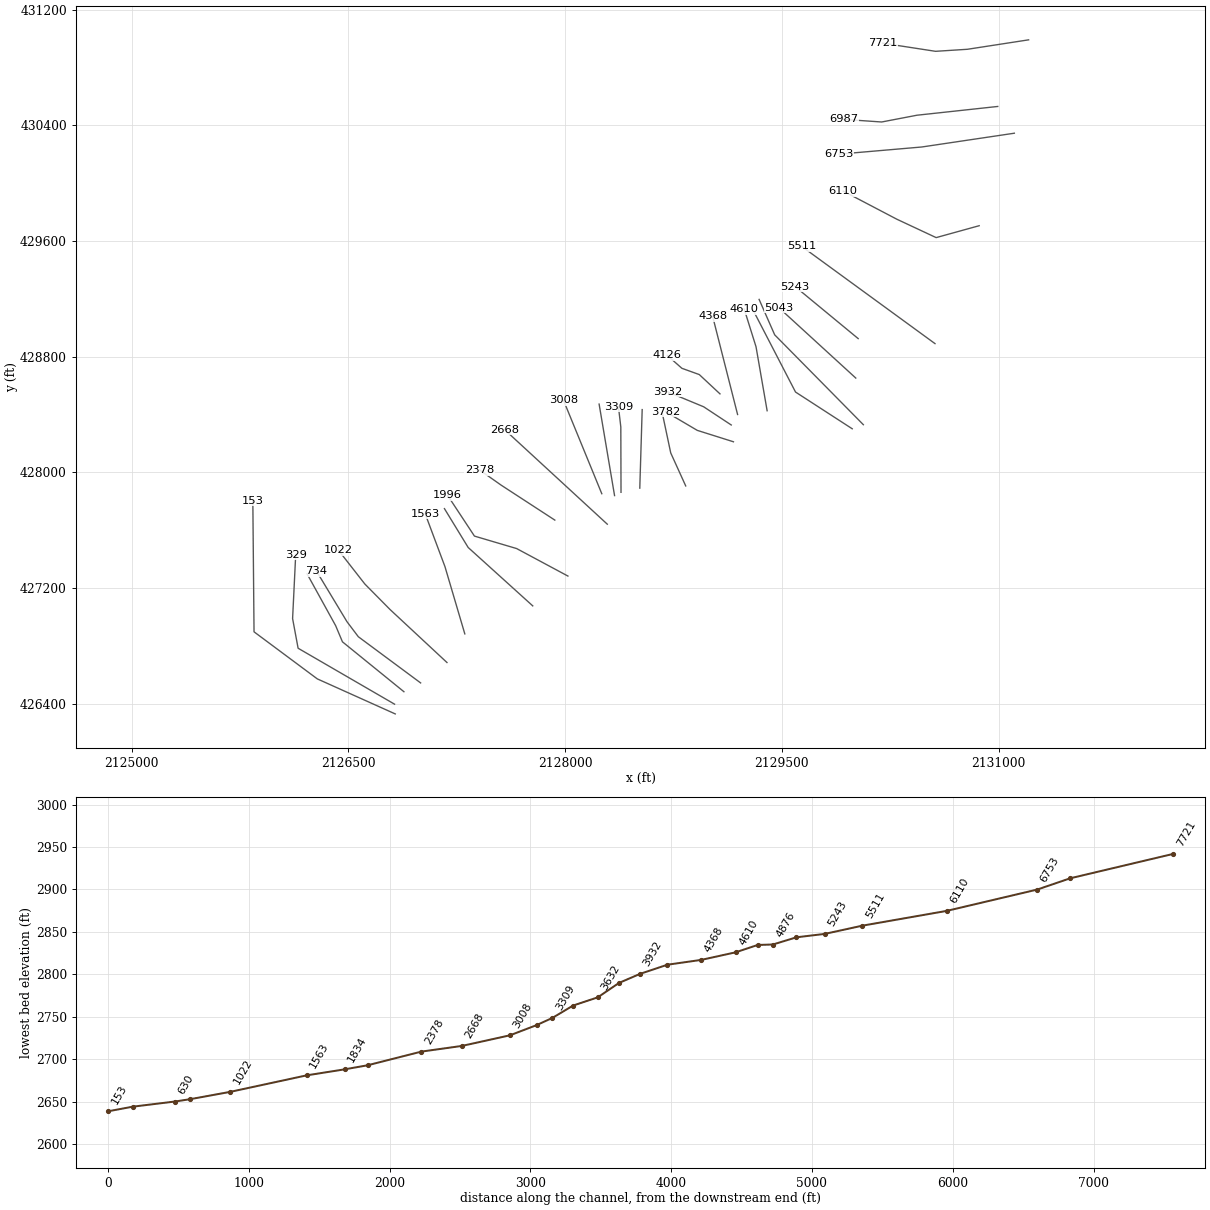
HEC-RAS study ROCKYRN.prj: ROCKYRN

--- ROCKYRN.g01 (geometry) --- (continued)

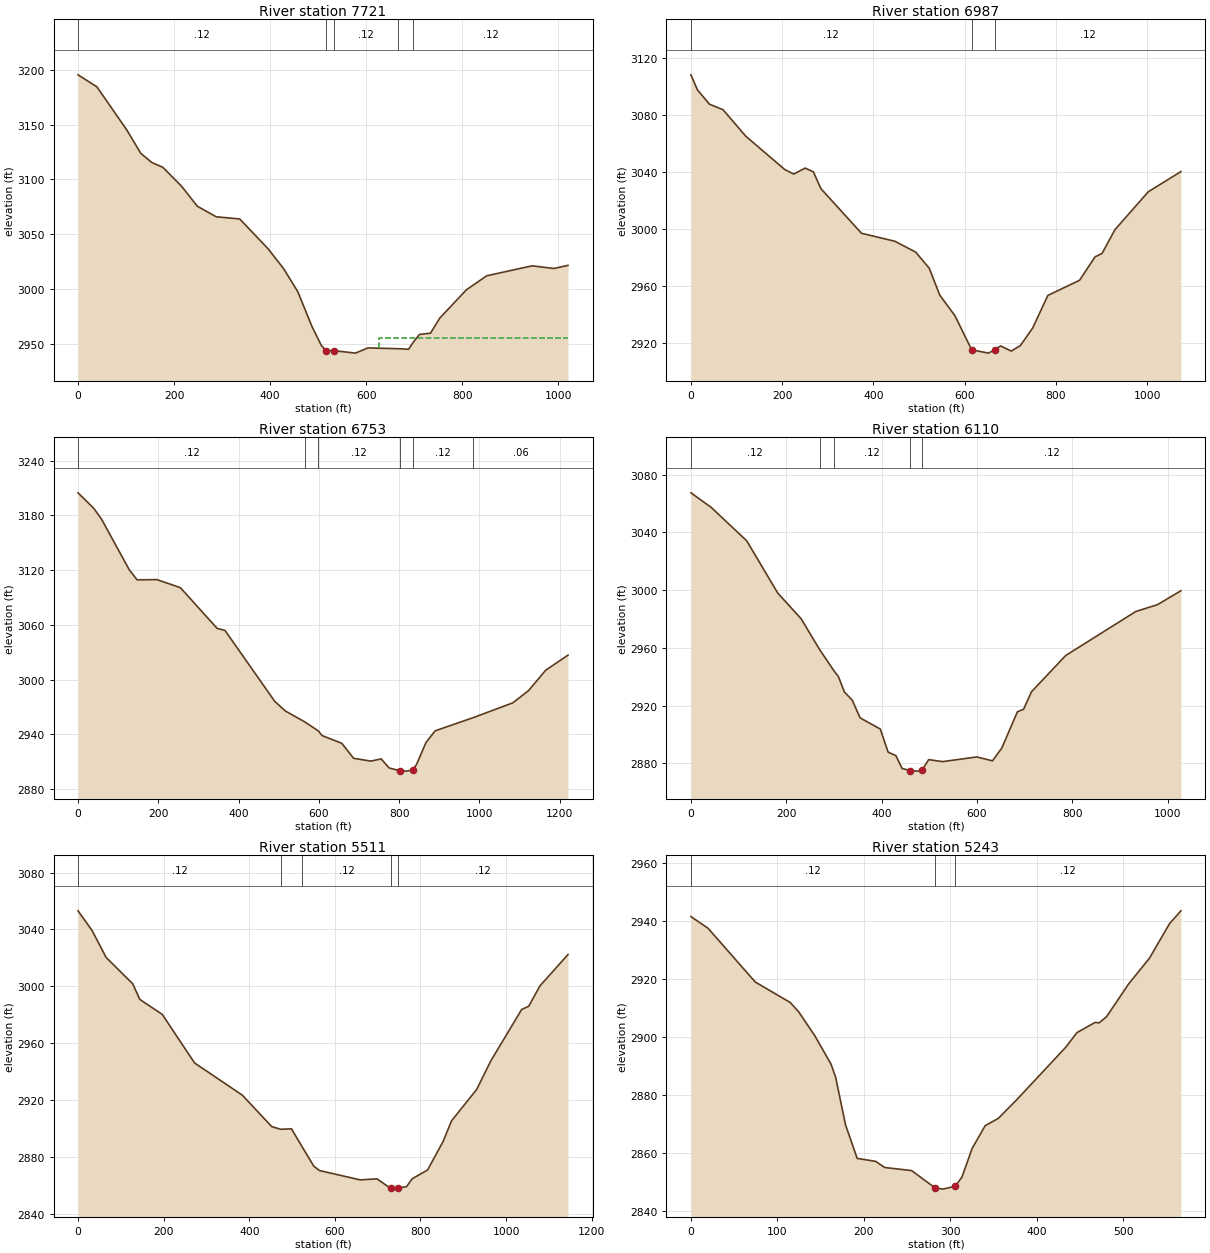
Type RM Length L Ch R = 1 ,7721    ,700.2,733.4,734.8
XS GIS Cut Line= 4
     2131207.494      430990.817     2130784.141      430925.551
     2130563.645      430911.439      2130196.74      430967.886
#Sta/Elev= 30
       0 3195.31    39.2 3184.42   101.4 3145.21   130.8 3123.75   153.7 3115.46
   176.6 3111.11   215.8 3093.77   248.5 3075.63   287.8 3066.05   336.8 3064.05
   395.7 3036.96   428.4 3018.66   457.6 2997.92   486.8 2966.56   506.3 2949.21
   516.1  2944.1   532.3 2944.17   577.8 2941.88   603.8 2946.63  667.27 2945.89
   688.4 2945.38  697.16 2951.19   711.2 2958.94     734 2960.01   753.5 2973.82
   808.9 2999.56   851.2 3012.31   945.6 3021.39   991.2 3018.95  1020.5 3021.82
#Mann= 5 ,-1 , 0
       0     .12       0   516.1     .04       0   532.3     .12       0
  667.27    .016       0  697.16     .12       0
#XS Ineff= 2 , 0
                          627.24         2956.08
Permanent Ineff=
       F       F
Bank Sta=516.1,532.3
XS Rating Curve= 0 ,0
Exp/Cntr=0.3,0.1

Type RM Length L Ch R = 1 ,6987    ,246.2,234.6,231.9
XS GIS Cut Line= 4
2130993.80260155430530.1772208252130434.81853725430469.580686934
2130190.41992176430422.7809520542129927.82140938430440.980848952
#Sta/Elev= 30
       0 3108.15    14.3 3097.57    40.7 3087.55    70.4  3083.7   120.2 3065.15
   205.7 3041.77   225.5  3038.6   250.6 3042.77   268.4 3040.17   284.9  3028.4
     374 2997.07   447.1  2991.5   492.8 2983.87   522.5 2972.61   545.6 2953.71
   578.8 2939.32   615.6 2915.39   652.3 2913.07   665.7 2915.36     679 2918.11
   702.4 2914.49   722.4 2918.41   749.2 2930.62   782.6 2953.52   852.1 2964.14
     886 2980.55   901.4 2982.96   929.7 2999.62  1002.9 3026.22  1074.3 3040.33
#Mann= 3 , 0 , 0
       0     .12       0   615.6     .04       0   665.7     .12       0
Bank Sta=615.6,665.7
XS Rating Curve= 0 ,0
Exp/Cntr(USF)=0,0
Exp/Cntr=0.3,0.1

Type RM Length L Ch R = 1 ,6753    ,644.4,642.3,628.9
XS GIS Cut Line= 3
     2131108.712      430345.205     2130468.391      430249.951
     2129896.865       430200.56
#Sta/Elev= 30
       0 3204.71    39.2 3187.73    58.8  3175.7   127.5 3120.52   147.1 3109.36
   196.2 3109.64     255 3100.82   346.6 3056.19   366.2 3053.93   490.4 2976.12
   516.6 2965.69  564.86 2953.77  598.89 2943.79   608.1 2938.75   657.2 2930.28
   686.7 2913.86   729.3 2910.77   755.5 2913.14   775.2 2903.25   802.5 2900.16
   817.5 2899.78   834.2 2900.89     844  2907.5     867 2931.07   889.9 2943.94
  984.64 2958.37  1083.4  2974.6  1122.7 2988.03  1165.3 3010.29    1221 3026.91
#Mann= 6 ,-1 , 0
       0     .12       0  564.86    .016       0  598.89     .12       0
   802.5     .04       0   834.2     .12       0  984.64     .06       0
Bank Sta=802.5,834.2
XS Rating Curve= 0 ,0
Exp/Cntr=0.3,0.1

Type RM Length L Ch R = 1 ,6110    ,599.2,599.2,590.7
XS GIS Cut Line= 4
      2130865.48      429705.668     2130567.565       429623.35
      2130295.13      429750.747     2129924.697      429944.784
#Sta/Elev= 30
       0 3067.37    42.3 3057.33   117.1 3034.14   182.2 2997.93     231 2980.27
  270.29 2958.72  300.93 2943.72   309.1 2940.38   322.2 2929.38   338.5 2923.79
   354.8 2911.59   397.3 2903.81   413.7 2887.83     430 2885.42   443.1 2876.52
   459.9 2875.08   475.8 2874.68   485.6 2875.74   498.7 2882.63   528.1 2881.26
     600  2884.5   632.7 2881.81   652.3 2890.72     685 2915.78     698 2917.52
   714.4  2929.6   786.2 2954.72   933.3 2985.19     979 2989.96    1028 2999.59
#Mann= 5 ,-1 , 0
       0     .12       0  270.29    .016       0  300.93     .12       0
   459.9     .04       0   485.6     .12       0
Bank Sta=459.9,485.6
XS Rating Curve= 0 ,0
Exp/Cntr=0.3,0.1

Type RM Length L Ch R = 1 ,5511    ,268.4,267.8,267.2
XS GIS Cut Line= 2
     2130559.725      428890.323     2129634.622      429564.551
#Sta/Elev= 30
       0 3053.11    32.8 3039.28    65.6 3020.31   127.9 3001.72   144.3 2990.77
   196.8 2980.23   272.2 2946.07   383.8  2923.4   452.6 2901.25  473.57 2899.39
   498.6 2899.72  523.72 2886.95     551 2873.34   564.2 2870.33   659.3 2863.78
   698.6  2864.5   730.3 2857.78     738 2857.27   747.8 2858.02   767.5 2858.99
   780.6 2864.56   816.7 2870.78   852.8 2890.76   872.5 2905.28   931.5  2927.5
   964.3 2947.51  1036.5 2983.72  1052.9 2985.97  1079.1  3000.3  1144.7 3022.37
#Mann= 5 ,-1 , 0
       0     .12       0  473.57    .016       0  523.72     .12       0
   730.3     .04       0   747.8     .12       0
Bank Sta=730.3,747.8
XS Rating Curve= 0 ,0
Exp/Cntr=0.3,0.1

Type RM Length L Ch R = 1 ,5243    ,200.8,200.5,198.8
XS GIS Cut Line= 2
2130028.21751709428924.9521772162129591.05673694429285.268288983
#Sta/Elev= 30
       0 2941.65    19.7 2937.64    74.4 2919.05   114.9 2911.97   124.6 2908.76
   143.2 2900.52   161.9 2890.76   167.3 2886.19   178.7  2869.8   192.2 2858.17
   213.7 2857.13     224 2855.03   255.2 2853.96     282 2848.04   291.1 2847.56
   305.52848.525   313.4 2851.75     325 2861.53   340.2 2869.47   355.3 2871.96
   376.3  2878.3   433.8 2896.69   446.2 2901.56   467.2  2905.1     472 2904.96
   480.5 2907.07     506 2918.37   530.1 2927.27   553.4 2939.23   566.5 2943.63
#Mann= 3 , 0 , 0
       0     .12       0     282     .04       0   305.5     .12       0
Bank Sta=282,305.5
XS Rating Curve= 0 ,0
Exp/Cntr(USF)=0,0
Exp/Cntr=0.3,0.1

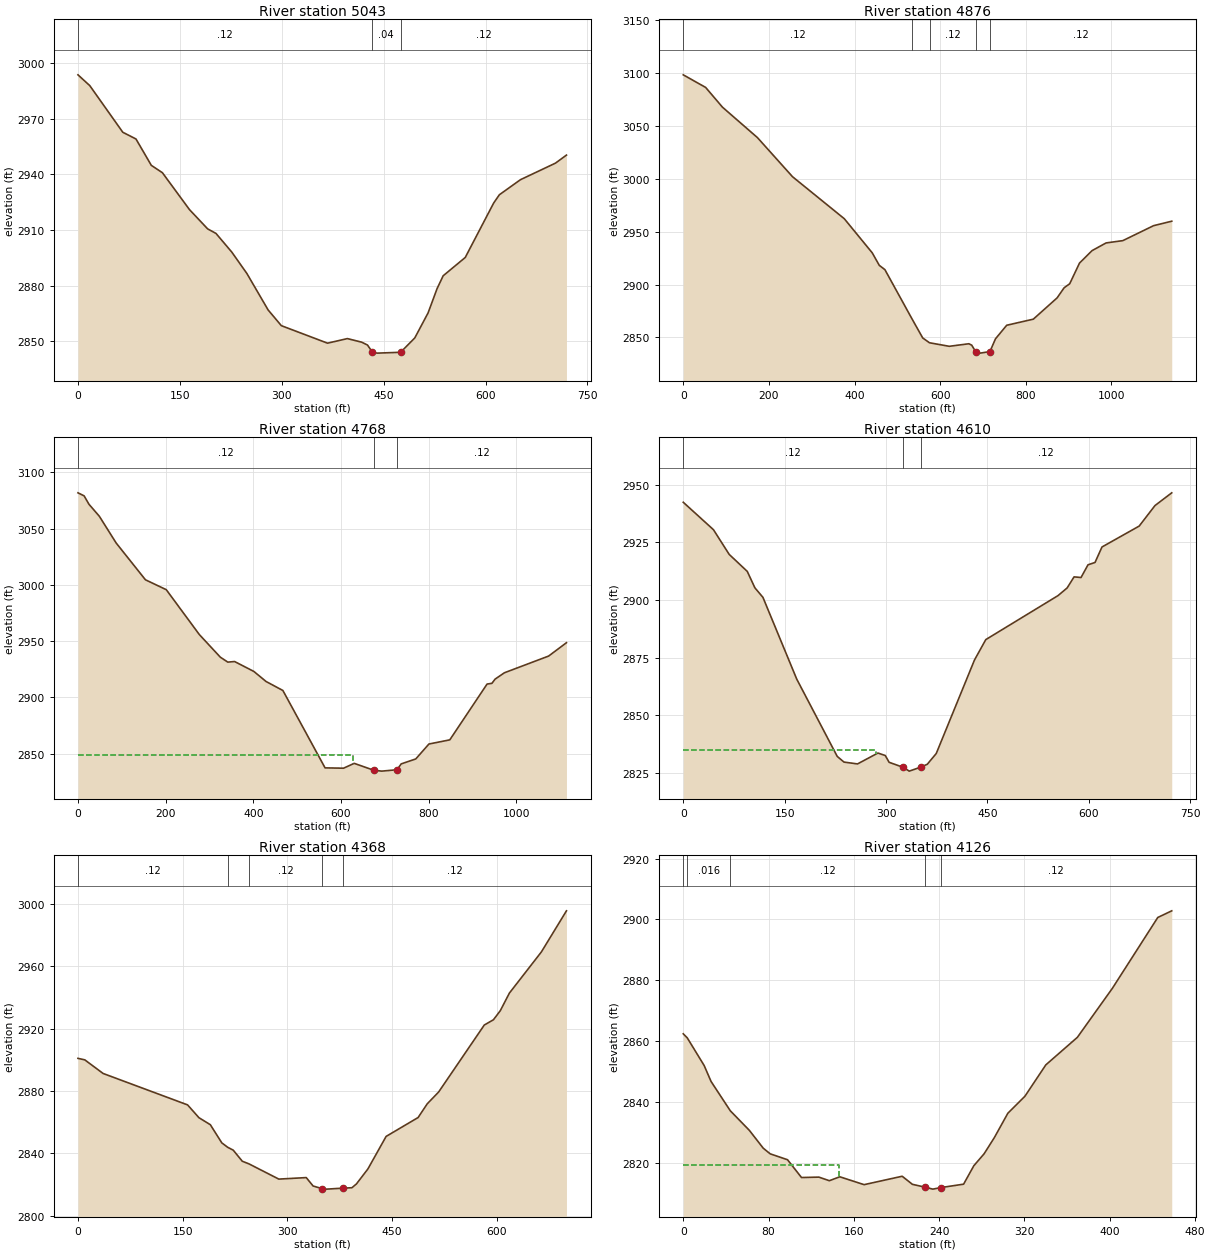
Type RM Length L Ch R = 1 ,5043    ,167.9,166.9,166.9
XS GIS Cut Line= 2
2130011.54794441 428652.164440822129480.83895088 429137.38409205
#Sta/Elev= 30
       0 2993.67    17.4 2987.84      66 2962.69    85.4 2959.06     108 2944.84
   124.3 2940.87   164.2 2920.96   190.9 2910.58   203.2 2908.12   226.5 2898.03
   248.7 2886.49   279.9 2866.86   299.4 2858.37   367.4 2848.93   396.6  2851.4
   417.6 2849.47   426.2 2847.93   432.92844.346   440.1 2843.56   474.9 2844.01
   495.8 2851.74   515.4 2865.26   528.7  2878.4   537.6 2885.28   570.1 2895.15
   611.9 2924.49   620.3 2928.97   651.4 2937.11   702.9 2946.03   719.1 2950.37
#Mann= 3 , 0 , 0
       0     .12       0   432.9     .04       0   474.9     .12       0
Bank Sta=432.9,474.9
XS Rating Curve= 0 ,0
Exp/Cntr(USF)=0,0
Exp/Cntr=0.3,0.1

Type RM Length L Ch R = 1 ,4876    ,115.3,108.5,102.7
XS GIS Cut Line= 3
     2130063.854      428329.773     2129450.385      428951.082
     2129342.587      429196.077
#Sta/Elev= 30
       0  3098.5    52.3 3086.57    91.6 3067.87   173.3 3039.06   255.1 3002.09
   376.1  2962.3   441.5 2929.92   457.8 2918.16   470.9 2914.11  533.05 2868.36
   559.2 2849.46  575.09 2844.88   621.3 2841.54   667.1 2843.96   673.7 2842.62
   683.5 2835.97   693.3 2835.08   716.2 2836.53   729.2 2848.65   755.4 2861.46
   817.5 2867.22   873.1 2887.38   889.5 2896.96   902.5 2900.73   925.4 2920.32
   954.7  2932.1   987.4 2939.37  1026.6 2941.56  1098.4 2955.72  1140.8 2959.95
#Mann= 5 ,-1 , 0
       0     .12       0  533.05    .016       0  575.09     .12       0
   683.5     .04       0   716.2     .12       0
Bank Sta=683.5,716.2
XS Rating Curve= 0 ,0
Exp/Cntr=0.3,0.1

Type RM Length L Ch R = 1 ,4768    ,162.9,157.2,146.1
XS GIS Cut Line= 3
  2129986.907884428301.5174272362129594.56230663428555.499588426
 2129296.9861924429129.802534999
#Sta/Elev= 30
       0 3081.75      14 3079.07    25.1 3071.59    48.6 3061.02    87.2 3037.14
   153.9 3004.51   201.4 2995.72   276.8 2955.87   324.7 2935.77   341.7 2931.37
   357.3 2931.88   401.2 2923.09   429.1 2914.15   467.4 2906.17   563.6 2837.44
   605.8 2837.14   630.1 2841.44   674.4 2835.37   692.9 2834.54   727.5 2835.75
   737.3 2840.97   770.5 2845.37   800.5 2858.62   848.1 2862.31   933.1 2911.87
   944.2 2912.53   951.4 2916.26   972.6  2921.9  1073.5 2936.75  1114.2 2948.61
#Mann= 3 , 0 , 0
       0     .12       0   674.4     .04       0   727.5     .12       0
#XS Ineff= 2 , 0
          628.25 2848.95
Permanent Ineff=
       F       F
Bank Sta=674.4,727.5
XS Rating Curve= 0 ,0
Exp/Cntr(USF)=0,0
Exp/Cntr=0.3,0.1

Type RM Length L Ch R = 1 ,4610    ,240.3,242.6,243
XS GIS Cut Line= 3
2129398.09123632428426.3156623532129321.24656794428868.599420399
2129239.27892166429129.871292913
#Sta/Elev= 30
       0 2942.41    44.7 2930.51      68  2919.8    94.7 2912.44     106 2905.31
   117.9 2901.18   167.9 2865.74   227.8 2832.24   237.8 2829.77   257.8 2828.97
     288 2833.69   298.9 2832.61   304.6 2829.67     325 2827.54   334.4 2825.85
     351 2827.55     361 2828.82   374.3 2833.49   430.9 2874.05   447.6 2882.87
   554.5 2901.95   567.9 2905.25   578.2 2910.06   588.5 2909.79   598.8 2915.29
   609.2 2916.31   619.5 2923.02   674.5 2932.08   697.9 2940.98   722.7  2946.5
#Mann= 3 , 0 , 0
       0     .12       0     325     .04       0     351     .12       0
#XS Ineff= 2 , 0
          285.22 2834.86
Permanent Ineff=
       F       F
Bank Sta=325,351
XS Rating Curve= 0 ,0
Exp/Cntr(USF)=0,0
Exp/Cntr=0.3,0.1

Type RM Length L Ch R = 1 ,4368    ,234.1,241.6,247.7
XS GIS Cut Line= 2
      2129193.63      428400.331     2129021.153      429078.479
#Sta/Elev= 30
       0 2900.99     9.8 2900.02      36 2891.28     157  2871.1   173.3 2862.86
   189.6 2858.37     206 2846.72  214.34 2843.89   222.4 2842.01   235.4 2834.89
  244.82 2833.23   287.7 2823.42     327 2824.39   336.8 2818.99   349.9 2817.27
   356.4 2816.98   379.3  2817.6   392.4 2817.87   398.9 2820.33   415.3 2829.95
   441.4 2850.85   487.2 2862.97   500.3 2871.79   516.6 2879.36     582  2922.4
   595.1 2925.78   604.9 2931.59     618 2942.94   663.8 2969.37   699.7 2995.76
#Mann= 5 ,-1 , 0
       0     .12       0  214.34    .016       0  244.82     .12       0
   349.9     .04       0   379.3     .12       0
Bank Sta=349.9,379.3
XS Rating Curve= 0 ,0
Exp/Cntr=0.3,0.1

Type RM Length L Ch R = 1 ,4126    ,197.1,194.1,192.8
XS GIS Cut Line= 4
     2129071.806      428542.901     2128928.643      428676.302
     2128808.256      428719.685     2128707.392      428808.619
#Sta/Elev= 30
       0 2862.38    3.74 2861.06    19.6 2851.95    26.1 2846.69   44.11 2837.06
      62 2830.61      75 2824.75    81.5 2822.89    97.8 2820.94   110.9 2815.09
   127.2 2815.22     137 2814.04   146.8 2815.33   169.6 2812.74   205.3 2815.51
   214.9 2812.85   226.4 2811.94   234.1 2811.27   241.4 2811.77   262.9  2812.9
   272.5 2818.97   282.1 2822.88   291.7  2828.2   304.4 2836.24   320.4 2841.83
     340 2852.15   369.6 2861.22   402.4 2877.34     445 2900.66   458.1 2902.85
#Mann= 5 ,-1 , 0
       0     .12       0    3.74    .016       0   44.11     .12       0
   226.4     .04       0   241.4     .12       0
#XS Ineff= 2 , 0
          145.88 2819.29
Permanent Ineff=
       F       F
Bank Sta=226.4,241.4
XS Rating Curve= 0 ,0
Exp/Cntr=0.3,0.1

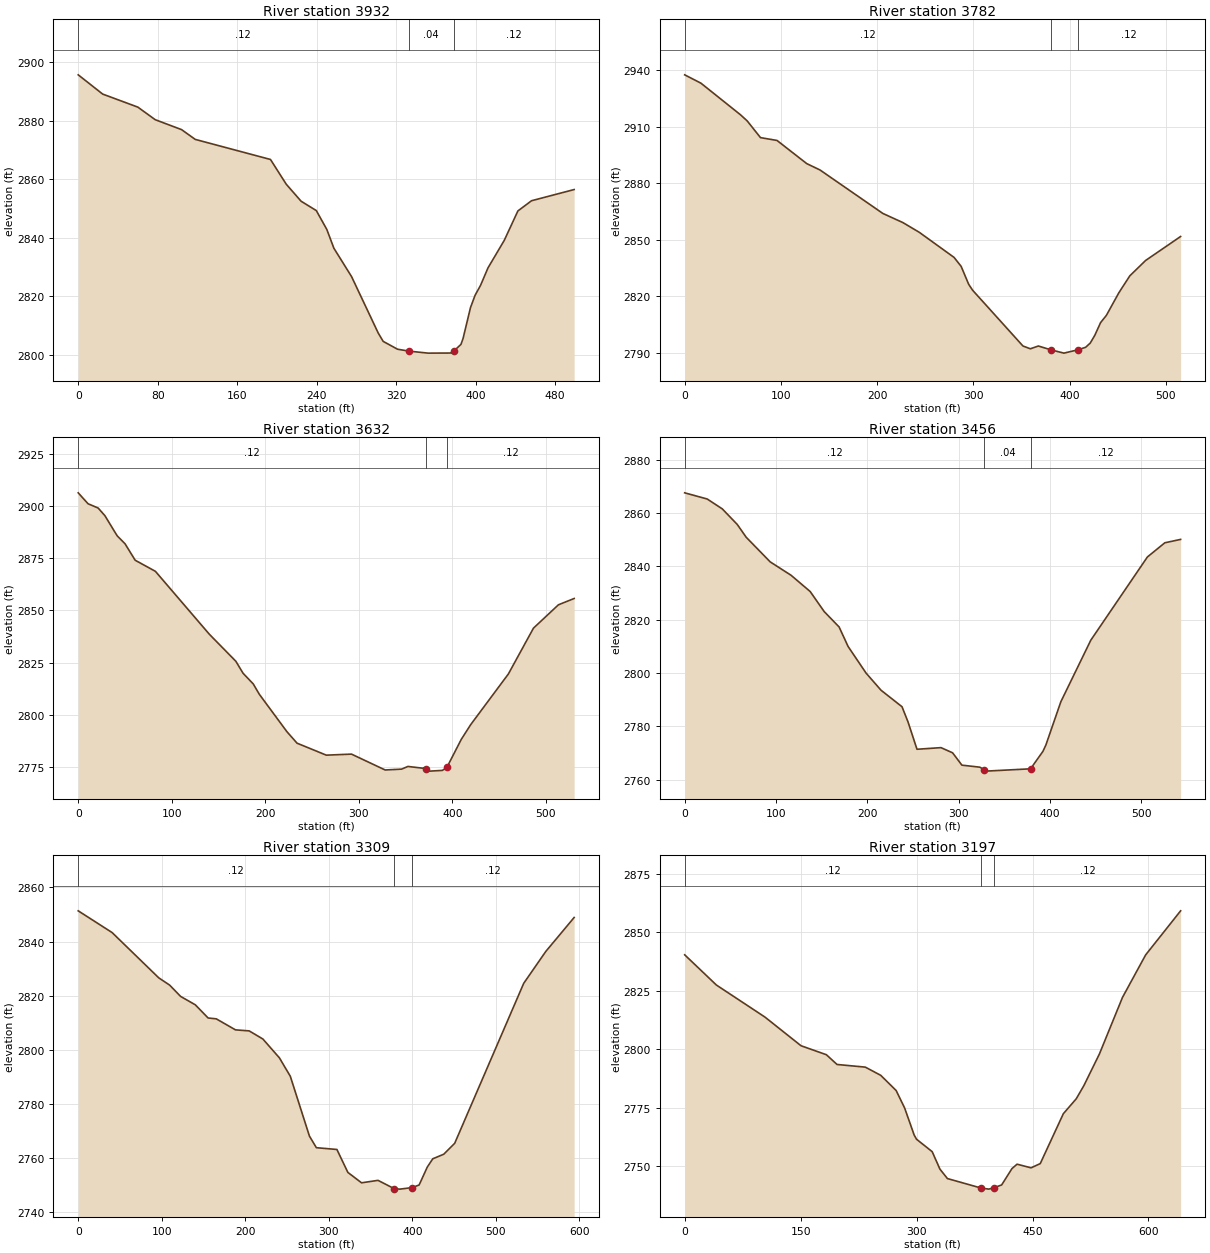
Type RM Length L Ch R = 1 ,3932    ,151.9,150.2,150.2
XS GIS Cut Line= 3
2129149.76777626428327.7557619122128959.08782566428453.493990205
2128708.99310785 428557.12439814
#Sta/Elev= 30
       0 2895.62    24.6 2889.04      60 2884.58    77.5 2880.28     104 2876.89
   117.8 2873.54   193.5 2866.68   209.3 2858.25   224.3 2852.41   239.6 2849.21
   250.2 2842.75   257.3 2836.34   275.1 2826.63   301.9 2807.36   306.9 2804.49
   321.3 2801.82   332.4 2801.17   352.1 2800.47   374.5  2800.5   378.1  2801.2
   385.2 2803.47   387.3 2805.47   394.8 2816.06   399.4 2820.25   404.9 2823.64
   412.4 2829.62   428.7 2838.98   442.5 2849.09   456.2 2852.57   499.1  2856.4
#Mann= 3 , 0 , 0
       0     .12       0   332.4     .04       0   378.1     .12       0
Bank Sta=332.4,378.1
XS Rating Curve= 0 ,0
Exp/Cntr(USF)=0,0
Exp/Cntr=0.3,0.1

Type RM Length L Ch R = 1 ,3782    ,163.9,150,146
XS GIS Cut Line= 3
2129164.96690276428211.6897050252128914.87218494428290.448815055
2128696.55745889428418.950520894
#Sta/Elev= 30
       0 2937.49    16.9 2933.06    58.1 2916.25      65 2913.02    78.8 2904.16
      96 2902.65   126.9 2890.35   140.7 2886.97     206  2863.9   226.9 2859.03
   243.9 2853.88     280 2840.57   287.4 2835.79   295.2  2826.3   299.3 2823.14
   351.6 2793.54   359.3 2792.06   367.6 2793.53   381.1 2791.43   394.2 2789.75
   408.9 2791.53   416.8 2792.86   421.6 2795.11   426.4  2799.3   432.3 2805.95
   438.3 2809.76   451.3 2821.79   462.7 2830.78   479.1 2838.93   515.5 2851.67
#Mann= 3 , 0 , 0
       0     .12       0   381.1     .04       0   408.9     .12       0
Bank Sta=381.1,408.9
XS Rating Curve= 0 ,0
Exp/Cntr(USF)=0,0
Exp/Cntr=0.3,0.1

Type RM Length L Ch R = 1 ,3632    ,182.3,175.5,172.9
XS GIS Cut Line= 3
2128834.73133614427906.325436312 2128731.1009282428134.312333768
2128673.06789976428407.896610714
#Sta/Elev= 30
       0 2906.51    10.5 2901.27    21.3 2899.21    28.5 2895.56    41.6 2885.89
    50.1 2882.01    60.9 2874.13    82.5 2868.81   140.2 2838.57   168.5  2825.6
   176.2 2819.85   187.1 2814.71   193.6 2809.74   223.1 2791.77   233.9 2786.26
   265.2  2780.5   292.1    2781   328.1 2773.38   345.7 2773.79   352.4 2775.08
   371.5 2774.07   375.9 2772.83   389.3 2773.18   394.1 2774.66   409.5 2788.12
   419.5 2795.15   459.8  2819.5   486.6  2841.5   513.3 2852.73   530.1 2855.75
#Mann= 3 , 0 , 0
       0     .12       0   371.5     .04       0   394.1     .12       0
Bank Sta=371.5,394.1
XS Rating Curve= 0 ,0
Exp/Cntr(USF)=0,0
Exp/Cntr=0.3,0.1

Type RM Length L Ch R = 1 ,3456    ,147.3,147.2,146.1
XS GIS Cut Line= 2
2128516.93141847427891.1263098152128533.51228374428434.149647391
#Sta/Elev= 30
       0 2867.65    24.7 2865.33    41.2 2861.62    57.6 2855.78    67.4 2850.97
    93.7 2841.72   116.6 2836.68   137.5 2830.59   152.8 2823.08   169.2 2817.27
     179 2809.97   198.7 2799.97   215.1 2793.53   238.1 2787.33   244.7  2781.6
   254.5 2771.36   280.8 2771.97   293.5 2770.03   303.7 2765.39   323.4 2764.63
   328.1 2763.68     330 2763.15   378.9 2764.02   392.5 2770.59   395.7 2772.96
   412.1 2789.21   444.9 2812.31   506.9 2843.56     526 2848.89   543.3 2850.16
#Mann= 3 , 0 , 0
       0     .12       0   328.1     .04       0   378.9     .12       0
Bank Sta=328.1,378.9
XS Rating Curve= 0 ,0
Exp/Cntr(USF)=0,0
Exp/Cntr=0.3,0.1

Type RM Length L Ch R = 1 ,3309    ,109.9,111.9,113.5
XS GIS Cut Line= 3
2128387.04797386427862.1097955942128385.66623509428313.938374187
2128369.08536982428454.875728978
#Sta/Elev= 30
       0 2851.35    40.6 2843.32    96.4 2826.61   109.5 2823.91   122.6 2819.74
   140.2 2816.64   155.5 2811.78   165.3 2811.46   188.3 2807.39   204.7 2807.01
   221.1 2804.01   240.8 2797.08   253.9 2790.27   276.8 2768.17   285.1 2763.88
   309.7 2763.22   322.8 2754.76   339.2 2750.91   358.9 2751.82   378.6 2748.71
   385.1 2748.58   399.6 2749.14   408.1  2750.1   417.9 2756.73   424.5 2759.79
   437.6 2761.47   450.7  2765.5   533.3 2824.57   559.7 2836.33   593.7 2848.89
#Mann= 3 , 0 , 0
       0     .12       0   378.6     .04       0   399.6     .12       0
Bank Sta=378.6,399.6
XS Rating Curve= 0 ,0
Exp/Cntr(USF)=0,0
Exp/Cntr=0.3,0.1

Type RM Length L Ch R = 1 ,3197    ,185.5,189.3,193.3
XS GIS Cut Line= 2
2128342.35393373427839.6086661712128235.46565036428472.271748801
#Sta/Elev= 30
       0 2840.42      41 2827.49   103.9 2813.75   150.5 2801.49   183.3 2797.65
   197.1 2793.47   233.7 2792.33   253.7 2788.81   273.6 2782.31   284.6  2774.8
   296.9 2763.26     300 2761.45   320.2 2756.14   330.2 2748.68   339.9 2744.63
   383.4 2740.57   393.4  2740.1   400.7 2740.75   410.1  2741.9   423.4 2748.89
     430 2750.78   448.1 2749.22     460 2751.03   489.9  2772.4   506.6 2778.79
   516.4 2784.39   536.5 2797.93   566.4 2822.19   596.4  2840.4   641.6 2859.25
#Mann= 3 , 0 , 0
       0     .12       0   383.4     .04       0   400.7     .12       0
Bank Sta=383.4,400.7
XS Rating Curve= 0 ,0
Exp/Cntr(USF)=0,0
Exp/Cntr=0.3,0.1

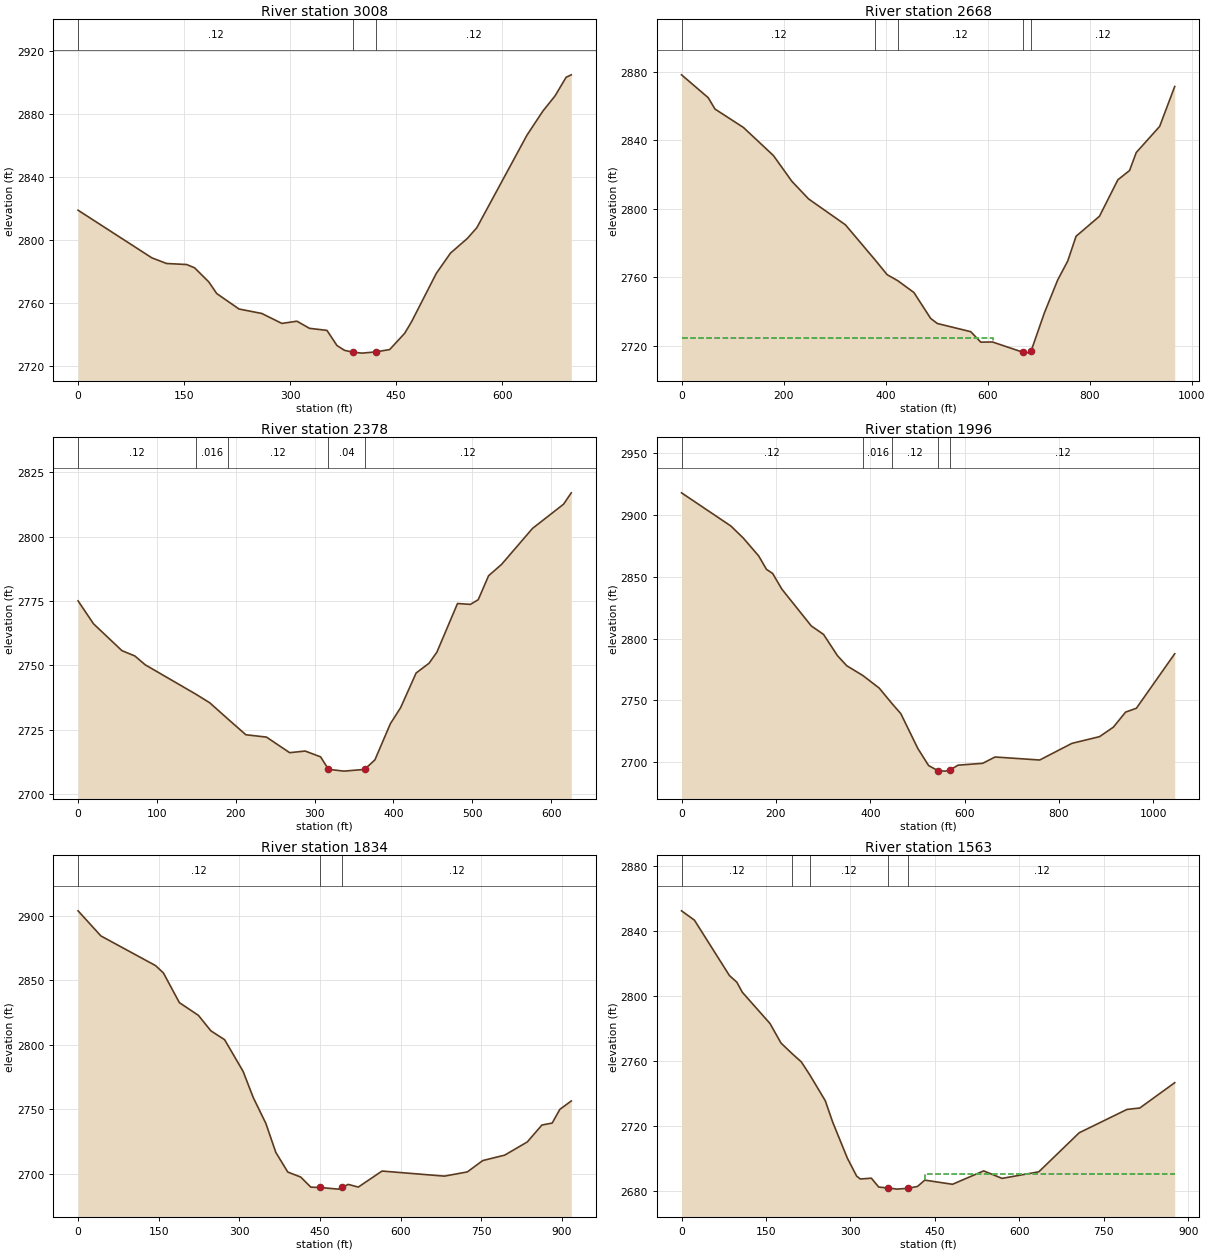
Type RM Length L Ch R = 1 ,3008    ,336.7,340.1,343
XS GIS Cut Line= 2
2128253.95950702427852.5421384012127989.27231591428498.037352847
#Sta/Elev= 30
       0 2818.92   104.4 2788.65   125.2 2785.06   153.5 2784.42   164.8 2782.33
   184.9 2773.38   196.1 2765.98   227.7 2756.13   259.9  2753.3   288.3 2746.98
   309.6 2748.39   327.3 2743.87   352.1 2742.55   366.3 2732.91   376.9 2729.89
   388.6 2728.72   401.8  2728.1   421.2 2728.88   440.8 2730.37     462 2740.69
   471.6 2747.89   506.8 2778.82   526.9 2791.69   550.7 2800.99   564.1  2807.8
     635  2866.6   657.7 2882.03   674.8 2891.61   690.4 2903.39   697.7 2904.96
#Mann= 3 , 0 , 0
       0     .12       0   388.6     .04       0   421.2     .12       0
Bank Sta=388.6,421.2
XS Rating Curve= 0 ,0
Exp/Cntr(USF)=0,0
Exp/Cntr=0.3,0.1

Type RM Length L Ch R = 1 ,2668    ,289.5,289.5,290.2
XS GIS Cut Line= 2
     2128292.046      427641.825     2127580.578      428296.453
#Sta/Elev= 30
       0 2878.25    52.4 2864.87    65.6 2858.26   121.3  2847.5   180.2 2831.07
   216.3 2816.04   249.1 2805.73   321.2 2790.64   380.1 2769.87   403.1 2761.47
  423.72 2757.99   455.6 2751.04   488.3 2735.94   501.4 2732.95     567 2728.16
   586.6 2722.05   609.6 2722.14   669.2 2716.16   675.1 2715.63     685  2716.6
   711.2 2739.06   737.4 2758.37   757.1 2769.47   773.4 2783.91   819.3 2795.61
   855.4 2816.92   878.3 2822.35   891.4 2832.85   937.3 2848.12   966.8 2871.44
#Mann= 5 ,-1 , 0
       0     .12       0   380.1    .016       0  423.72     .12       0
   669.2     .04       0     685     .12       0
#XS Ineff= 2 , 0
          611.36  2724.6
Permanent Ineff=
       F       F
Bank Sta=669.2,685
XS Rating Curve= 0 ,0
Exp/Cntr=0.3,0.1

Type RM Length L Ch R = 1 ,2378    ,373.8,382,386.8
XS GIS Cut Line= 3
     2127929.009      427670.113     2127558.561      427911.128
     2127408.299      428016.757
#Sta/Elev= 30
       0 2775.04    19.6 2766.12    55.6  2755.7      72 2753.64    85.1 2750.21
  149.25 2738.81     167 2735.44  190.32 2729.07   212.8 2723.02     239  2722.1
   268.4 2716.05   288.1 2716.68   307.7 2714.41   317.6 2709.58   337.2 2708.88
   363.4 2709.55   376.5 2713.24   396.1 2727.28   409.2 2733.58   428.8 2747.01
   445.2  2750.8   455.1 2755.07   481.3 2774.01   497.7 2773.68   507.6  2775.5
   520.7  2784.8   537.1 2789.18   576.4 2803.18   615.8  2812.6   625.6 2817.02
#Mann= 5 ,-1 , 0
       0     .12       0  149.25    .016       0  190.32     .12       0
   317.6     .04       0   363.4     .12       0
Bank Sta=317.6,363.4
XS Rating Curve= 0 ,0
Exp/Cntr=0.3,0.1

Type RM Length L Ch R = 1 ,1996    ,169.9,162.4,163.9
XS GIS Cut Line= 4
      2128019.61      427283.151     2127664.857      427473.268
     2127372.822      427559.506     2127186.625      427841.741
#Sta/Elev= 30
       0  2918.1   104.7 2891.21   130.9 2881.48   163.6 2866.97     180 2856.16
   193.1 2852.82   212.7 2840.09   274.9 2810.37     301 2803.45   330.5 2786.24
   350.1 2778.11  384.32 2770.18   418.9 2760.01  446.31 2747.35   464.7 2739.33
   500.7 2711.18   523.6 2697.29   543.3 2693.17   559.6 2692.78   569.5  2693.8
   585.8 2697.59   638.2  2699.1   664.4 2704.22     759 2701.78   827.3 2715.26
   885.8  2720.7   915.1 2728.38   941.1 2740.59   963.8 2743.66  1045.1 2787.82
#Mann= 5 ,-1 , 0
       0     .12       0  384.32    .016       0  446.31     .12       0
   543.3     .04       0   569.5     .12       0
Bank Sta=543.3,569.5
XS Rating Curve= 0 ,0
Exp/Cntr=0.3,0.1

Type RM Length L Ch R = 1 ,1834    ,281.1,270.9,259.9
XS GIS Cut Line= 3
2127776.22320308 427076.940036692127329.46099999427480.714811306
 2127165.1876126427749.386239282
#Sta/Elev= 30
       0 2903.77    42.5 2884.29   144.2 2861.28   158.7  2855.6   188.4 2832.59
   223.8 2822.72     247 2810.72   272.5 2803.86   306.8 2779.37   325.9 2758.86
   349.2 2738.96   367.7  2716.5     390 2701.23     414 2697.38   432.8 2689.54
   449.72689.279   483.9 2688.01   491.3 2689.44   502.4 2691.68   521.1  2689.6
   565.2 2702.03   681.1 2698.09   723.8 2701.35   752.5 2710.16   793.3 2714.36
   835.3 2724.58   862.5 2737.69   881.6 2739.23   895.9 2749.88   917.1 2756.35
#Mann= 3 , 0 , 0
       0     .12       0   449.7     .04       0   491.3     .12       0
Bank Sta=449.7,491.3
XS Rating Curve= 0 ,0
Exp/Cntr(USF)=0,0
Exp/Cntr=0.3,0.1

Type RM Length L Ch R = 1 ,1563    ,534.5,541.2,553.1
XS GIS Cut Line= 3
     2127306.183      426883.318     2127168.986       427347.83
     2127031.788      427714.344
#Sta/Elev= 30
       0 2852.22    22.9 2846.49    85.1 2812.37    98.2 2808.29     108 2802.08
   157.1 2782.84   176.7  2770.8  196.92 2764.12   212.7 2759.24  227.72 2751.25
   255.3 2735.29   268.4 2722.15   294.5 2699.94   310.9 2688.95   317.4 2687.13
   337.1 2687.63   350.2 2682.14   366.5 2681.63   382.9 2680.89   402.5 2681.43
   418.9 2682.53     432 2686.43   481.1 2683.87   536.5 2692.12   569.1  2687.5
   634.4 2691.55   706.1 2715.58   790.9 2729.95   813.7 2730.83   875.7 2746.41
#Mann= 5 ,-1 , 0
       0     .12       0  196.92    .016       0  227.72     .12       0
   366.5     .04       0   402.5     .12       0
#XS Ineff= 2 , 0
                             433         2690.45
Permanent Ineff=
       F       F
Bank Sta=366.5,402.5
XS Rating Curve= 0 ,0
Exp/Cntr=0.3,0.1

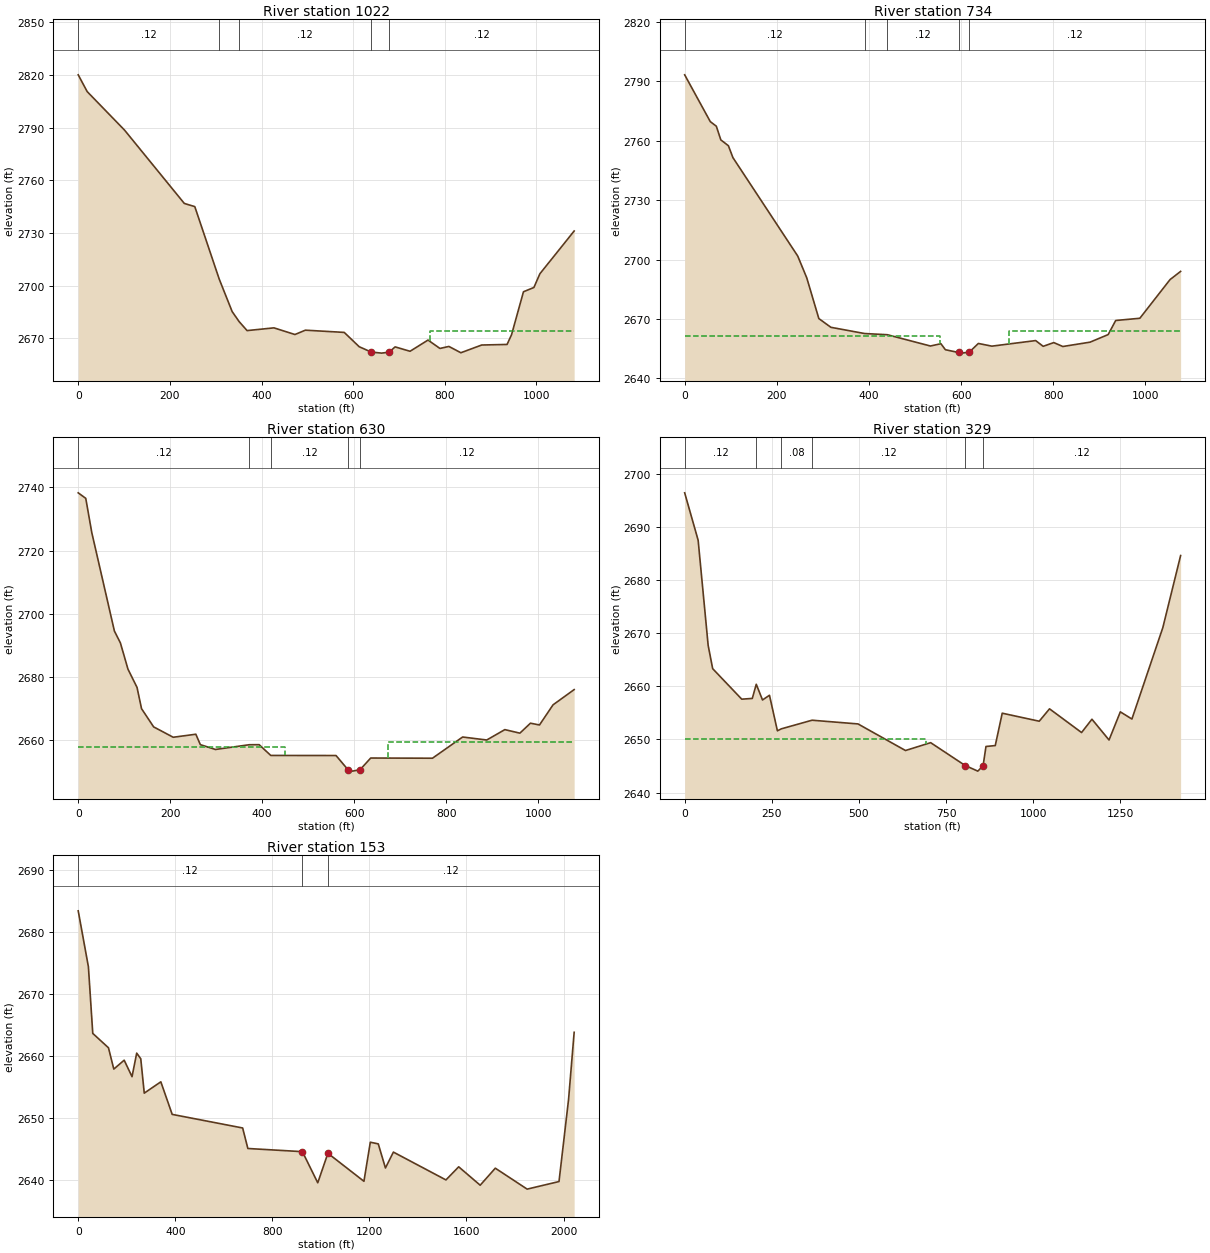
Type RM Length L Ch R = 1 ,1022    ,287.3,287.5,284.6
XS GIS Cut Line= 4
     2127182.705      426685.362     2126788.752      427051.875
     2126614.315      427228.272     2126432.039      427461.508
#Sta/Elev= 30
       0    2820    19.6 2810.44   101.1 2788.51   231.5 2746.76   254.4 2744.94
   307.7 2703.66   335.9 2685.19  351.07 2679.48   368.5 2674.33   427.2 2675.89
   472.9  2672.1   495.7 2674.57   580.5  2673.3   613.2 2665.14   639.3 2662.11
   662.1  2661.5   678.4 2662.05   691.5 2665.06   724.1 2662.56   763.3 2668.94
   789.4 2664.16   808.9 2665.31     835 2661.72   880.5 2666.12   935.8 2666.44
   945.6 2671.98   971.6 2696.44   994.4 2698.89  1007.4 2706.68  1082.2 2731.05
#Mann= 5 ,-1 , 0
       0     .12       0   307.7    .016       0  351.07     .12       0
   639.3     .04       0   678.4     .12       0
#XS Ineff= 2 , 0
                          766.78         2673.94
Permanent Ineff=
       F       F
Bank Sta=639.3,678.4
XS Rating Curve= 0 ,0
Exp/Cntr=0.3,0.1

Type RM Length L Ch R = 1 ,734     ,105.8,104.8,100.1
XS GIS Cut Line= 4
     2127000.428      426544.244     2126569.236      426863.719
     2126490.838      426967.597     2126279.161      427318.431
#Sta/Elev= 30
       0 2793.18    55.6 2769.57    68.7 2767.25    78.5 2760.34    94.9 2757.42
   104.7 2751.42   245.4 2701.76     265 2690.75   291.2 2670.22   317.4  2665.8
  390.66 2662.66  439.74 2662.07   533.4 2656.37   556.2 2657.53   565.9  2654.5
   594.4  2653.1   601.7 2652.78     618 2653.32   637.5 2657.66   666.8  2656.3
   761.8 2659.11   778.2 2656.21   801.2  2658.1   820.8 2656.12   879.9 2658.31
   919.2 2662.13   935.6 2669.24     988 2670.37  1053.6 2689.89  1076.5 2694.01
#Mann= 5 ,-1 , 0
       0     .12       0  390.66    .016       0  439.74     .12       0
   594.4     .04       0     618     .12       0
#XS Ineff= 2 , 0
          554.15 2661.49  704.32          2664.1
Permanent Ineff=
       F       F
Bank Sta=594.4,618
XS Rating Curve= 0 ,0
Exp/Cntr=0.3,0.1

Type RM Length L Ch R = 1 ,630     ,301.9,300.5,298.5
XS GIS Cut Line= 4
     2126884.791      426483.485     2126459.478      426828.439
     2126412.439      426940.157     2126214.482      427298.831
#Sta/Elev= 30
       0 2738.29    16.4 2736.54    29.5 2725.71    78.7 2694.51    91.8 2690.72
   108.2 2682.43   127.9 2676.65   137.7 2669.91     164 2664.14   206.6 2660.85
   255.8 2661.81   265.6 2658.51   298.4 2656.98  371.87 2658.48   393.5  2658.5
  418.76 2655.09   560.7 2655.06   586.9 2650.53   596.8 2650.12   613.1  2650.6
   636.1 2654.27   770.4 2654.21     836 2660.93   888.4 2659.98   927.8 2663.27
   960.5 2662.15   983.5 2665.31  1003.1 2664.74  1032.6 2671.12  1078.5 2675.95
#Mann= 5 ,-1 , 0
       0     .12       0  371.87    .016       0  418.76     .12       0
   586.9     .04       0   613.1     .12       0
#XS Ineff= 2 , 0
             450 2657.81  673.75         2659.24
Permanent Ineff=
       F       F
Bank Sta=586.9,613.1
XS Rating Curve= 0 ,0
Exp/Cntr=0.3,0.1

Type RM Length L Ch R = 1 ,329     ,176.1,176.1,176.1
XS GIS Cut Line= 4
     2126820.112      426397.2472126152.62198234426784.100107636
     2126114.524      426989.156     2126136.084      427432.109
#Sta/Elev= 30
       02696.422  38.6382687.502   67.372667.716   80.352663.321 163.7742657.577
  194.112657.718 205.4872660.383 223.4132657.427 243.4072658.313 266.1592651.619
 277.5352651.994 365.5742653.615 497.4722652.916 633.8322647.911 706.033 2649.39
   805.3 2645.08 841.4362644.031 856.5872645.033 864.794 2648.67  891.492648.844
 911.5122654.9361017.6972653.4271047.2592655.7581139.2312651.2951169.0372653.801
1218.0642649.8941250.4762655.1861283.759 2653.841372.4462671.0411423.5332684.612
#Mann= 6 ,-1 , 0
       0     .12       0 205.487    .016       0 277.535     .08       0
 365.574     .12       0   805.3     .04       0 856.587     .12       0
#XS Ineff= 2 , 0
           692.8 2650.13
Permanent Ineff=
       F       F
Bank Sta=805.3,856.587
XS Rating Curve= 0 ,0
Exp/Cntr=0.3,0.1

Type RM Length L Ch R = 1 ,153     ,152,153,151
XS GIS Cut Line= 4
2126824.97346443426329.7852598052126285.35948689426572.207456059
2125847.65368772426897.5962954492125839.39508773427804.390573749
#Sta/Elev= 30
       0 2683.35      42 2674.35      60 2663.62   124.7 2661.31   146.7 2657.88
   189.4 2659.31   221.8 2656.66     241 2660.45   257.8 2659.54   272.2 2654.01
   340.5 2655.83   387.3 2650.59   677.7  2648.4   699.1  2645.1   923.9 2644.59
   987.2 2639.58    1029 2644.33  1177.5 2639.82  1203.8 2646.11  1236.6 2645.84
  1266.1 2641.96  1298.9 2644.52  1515.5 2640.04    1568 2642.15  1656.6 2639.19
  1718.9 2641.93  1850.1 2638.56  1981.4 2639.78  2020.8    26532043.802  2663.8
#Mann= 3 , 0 , 0
       0     .12       0   923.9     .04       0    1029     .12       0
Bank Sta=923.9,1029
XS Rating Curve= 0 ,0
Exp/Cntr(USF)=0,0
Exp/Cntr=0.3,0.1
LCMann Table=0

Chan Stop Cuts=-1
Use User Specified Reach Order=0
Composite Channel Slope=5